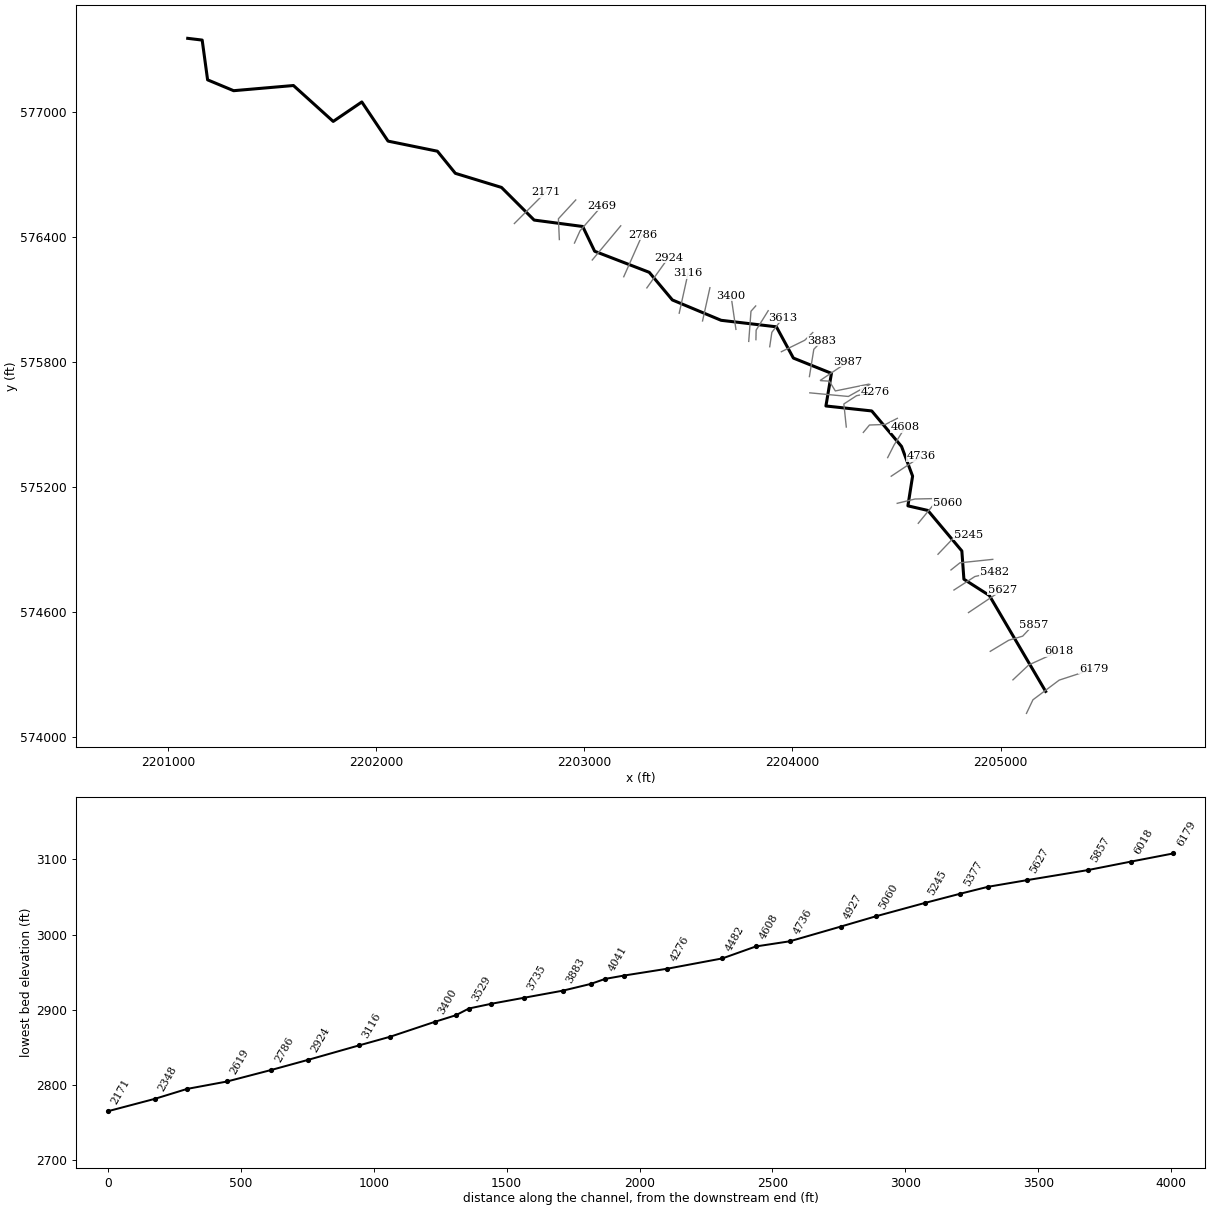
--- FLINTRN.prj (project) ---

Proj Title=FLINTRN
Current Plan=p01
Default Exp/Contr=0,0
English Units
Geom File=g01
Flow File=f01
Plan File=p01
BEGIN DESCRIPTION:
----------MODEL BY WOOD PLC 2022----------
AFH study
Randolph County, WV
HEC-RAS Version: RAS 6.2
Vertical Datum: NAVD88
Projection: NAD 1983 StatePlane West Virginia S FIPS 4702 (US Feet)
Terrain: 1-meter LIDAR (FEMA Region III 3DEP collected 2016-2018)
Land Use: 2019 NLCD
Hydrologic Method:
WV SIR2010-5033 regression equations
Additional Model Notes:
None
END DESCRIPTION:
DSS File=dss
DSS Export Rating Curves= 0
DSS Export Rating Curve Sorted= 0
DSS Export Volume Flow Curves= 0
DXF OffsetX= 0
DXF OffsetY= 0
DXF ScaleX= 0
DXF ScaleY= 0

--- FLINTRN.p01 (plan) ---

Plan Title=Floodplain
Program Version=6.20
Short Identifier=Floodplain
Geom File=g01
Flow File=f01
Subcritical Flow
K Sum by GR= 0
Std Step Tol= 0.01
Critical Tol= 0.01
Num of Std Step Trials= 20
Max Error Tol= 0.3
Flow Tol Ratio= 0.001
Split Flow NTrial= 30
Split Flow Tol= 0.02
Split Flow Ratio= 0.02
Log Output Level= 0
Friction Slope Method= 1
Unsteady Friction Slope Method= 2
Unsteady Bridges Friction Slope Method= 1
Parabolic Critical Depth
Global Vel Dist= 0 , 0 , 0
Global Log Level= 0
CheckData=True
Encroach Param=-1 ,0,0, 0
Computation Interval=0.1SEC
Output Interval=1SEC
Instantaneous Interval=Max Profile
Mapping Interval=1HOUR
Computation Time Step Use Courant=        0
Computation Time Step Use Time Series=    0
Computation Time Step Count To Double=0
Computation Time Step Max Doubling=0
Computation Time Step Max Halving=0
Computation Time Step Residence Courant=0
Run HTab= 0
Run UNet= 0
Run Sediment= 0
Run PostProcess= 0
Run WQNet= 0
Run RASMapper=-1
UNET Theta= 0
UNET Theta Warmup= 0
UNET ZTol= 0
UNET ZSATol= 0
UNET MxIter= 0
UNET Max Iter WO Improvement= 0
UNET MaxInSteps= 0
UNET DtIC= 0
UNET DtMin= 0
UNET MaxCRTS= 0
UNET WFStab= 0
UNET SFStab= 0
UNET WFX= 1
UNET SFX= 1
UNET Gravity=32.174
UNET 1D Methodology=Finite Difference
UNET DSS MLevel= 1
UNET Pardiso=0
UNET DZMax Abort= 0
UNET Use Existing IB Tables= 0
UNET Froude Reduction=False
UNET Froude Limit= 0
UNET Froude Power= 0
UNET D1 Cores= 0
UNET WindReference=Eulerian
UNET WindDragFormulation=Hsu (1988)
UNET D2 Coriolis=0
UNET D2 Cores= 0
UNET D2 Theta= 1
UNET D2 Theta Warmup= 1
UNET D2 Z Tol= 0.01
UNET D2 Volume Tol= 0.01
UNET D2 Max Iterations= 20
UNET D2 Equation= 0
UNET D2 RampUpFraction=0.1
UNET D2 TimeSlices= 1
UNET D2 Turbulence Formulation=Non-Conservative (original)
UNET D2 Eddy Viscosity=0.3
UNET D2 Transverse Eddy Viscosity=0.1
UNET D2 Smagorinsky Mixing=0
UNET D2 BCVolumeCheck=0
UNET D2 Cores=0
UNET D2 SolverType=PARDISO (Direct)
UNET D2 Minimum Iterations= 2147483647
UNET D2 Maximum Iterations= 2147483647
UNET D2 Restart Number= 10
UNET D2 Relaxation Coeff=1.3
UNET D2 SOR Precondition Iterations= 10
UNET D2 ILUT Maximum Fill= 8
UNET D2 ILUT Tolerance=1E-08
UNET D1D2 MaxIter= 0
UNET D1D2 ZTol=0.01
UNET D1D2 QTol=0.1
UNET D1D2 MinQTol=1
DSS File=dss
Write IC File= 0
Write IC File at Fixed DateTime=0
Write IC File at Sim End=0
Echo Input=False
Echo Parameters=False
Echo Output=False
Write Detailed= 0
HDF Write Warmup=0
HDF Write Time Slices=0
HDF Flush=0
HDF Compression= 1
HDF Chunk Size= 1
HDF Spatial Parts= 1
HDF Use Max Rows=0
HDF Fixed Rows= 1
Calibration Method= 0
Calibration Iterations= 20
Calibration Max Change=0.05
Calibration Tolerance=0.2
Calibration Maximum=1.5
Calibration Minimum=0.5
Calibration Optimization Method= 1
WQ AD Non Conservative
WQ ULTIMATE=-1
WQ Max Comp Step=1HOUR
WQ Output Interval=15MIN
WQ Output Selected Increments= 0
WQ Output face flow=0
WQ Output face velocity=0
WQ Output face area=0
WQ Output face dispersion=0
WQ Output cell volume=0
WQ Output cell surface area=0
WQ Output cell continuity=0
WQ Output cumulative cell continuity=0
WQ Output face conc=0
WQ Output face dconc_dx=0
WQ Output face courant=0
WQ Output face peclet=0
WQ Output face adv mass=0
WQ Output face disp mass=0
WQ Output cell mass=0
WQ Output cell source sink temp=0
WQ Output nsm pathways=0
WQ Output nsm derived pathways=0
WQ Create Restart=0
WQ Fixed Restart=0
WQ System Summary=0
WQ Write To DSS=0
Sorting and Armoring Iterations= 10
XS Update Threshold= 0.02
Bed Roughness Predictor= 0
Hydraulics Update Threshold= 0.02
Energy Slope Method= 1
Volume Change Method= 1
Sediment Retention Method= 0
Sediment TS Multiplier= 1
Warm Up Method= 0
XS Weighting Method= 0
Number of US Weighted Cross Sections= 1
Number of DS Weighted Cross Sections= 1
Upstream XS Weight=0
Main XS Weight=1
Downstream XS Weight=0
Number of DS XS's Weighted with US Boundary= 1
Upstream Boundary Weight= 1
Weight of XSs Associated with US Boundary= 0
Number of US XS's Weighted with DS Boundary= 1
Downstream Boundary Weight= 0.5
Weight of XSs Associated with DS Boundary= 0.5
Percentile Method= 0
Sediment Output Level= 3
Mass or Volume Output= 0
Output Increment Type= 1
Profile and TS Output Increment= 1
Transport Output Increment 1
XS Output Flag= 0
XS Output Increment= 10
Read HDF5 Sediment Hotstart= 0
Sediment Hotstart Type= 0
Write Gradation File= 0
Read Gradation Hotstart= 0
Write HDF5 File= 1
Write Binary Output= 1
Write DSS Sediment File= 0
DSS Sediment Output Type= 1
SV Curve= 0
Specific Gage Flag= 0
Subcell Erosion Methods= 0
Subcell Deposition Methods= 0
Advection Scheme= 1
Matrix Solver= 0
Implicit Weighting Factor= 1
Maximum Outer Loop Convergence Iterations= 5
Convergence Maximum Absolute= 0.001
Convergence RMSE= 0.0001
Grain Fractions Max Abs Error= 0.001
Max Subgrid Regions= 1
Max Subgrid Length Scale= 3.402823E+38
Initial Layer Thickness= 3.402823E+38
Min Layer Thickness= 3.402823E+38
Max Layer Thickness= 3.402823E+38
Number of Layers= 5

--- FLINTRN.f01 (steady flow) ---

Flow Title=Flow
Program Version=6.20
Number of Profiles= 1
Profile Names=P100yr
River Rch & RM=FLINTRN,Main,6179
     377
River Rch & RM=FLINTRN,Main,3234
     423
Boundary for River Rch & Prof#=FLINTRN,Main            , 1
Up Type= 0
Dn Type= 3
Dn Slope=0.18809
DSS Import GetInterval= 0
DSS Import GetPeak= 0
DSS Import FillOption= 0

--- FLINTRN.g01 (geometry) ---

Geom Title=Geometry
Program Version=6.20

River Reach=FLINTRN         ,Main
Reach XY= 30
2205215.95246462574218.2100818742204945.54887016574678.920052076
2204823.31914441574757.1360976872204813.46000002574892.864000008
     2204650.266      575087.3092204554.38700002575109.436000019
2204576.91500001575252.2389999932204523.78998899575394.669394127
2204380.73500003575565.1730000082204160.68200003575589.045000002
2204187.15800002575745.7290000022204004.43200003575819.079000011
2203922.83500002575969.2530000212203657.21000004576000.503000006
2203423.26900001576098.1590000092203312.15799999576230.972000018
2203050.00600003576332.1000000092202992.71400003576451.024000019
2202759.40200001576481.8509999962202602.63100003576638.621000007
2202381.04212774576706.3397023722202294.81900004576812.580000013
2202057.83999999 576861.017000022201931.79800002577049.038000017
2201794.44106384576955.6243831272201603.48126715577128.059076878
2201316.17299999577103.2050000132201191.17300004577155.288000003
 2201165.1441469577346.2613349712201095.70500003577354.643000022

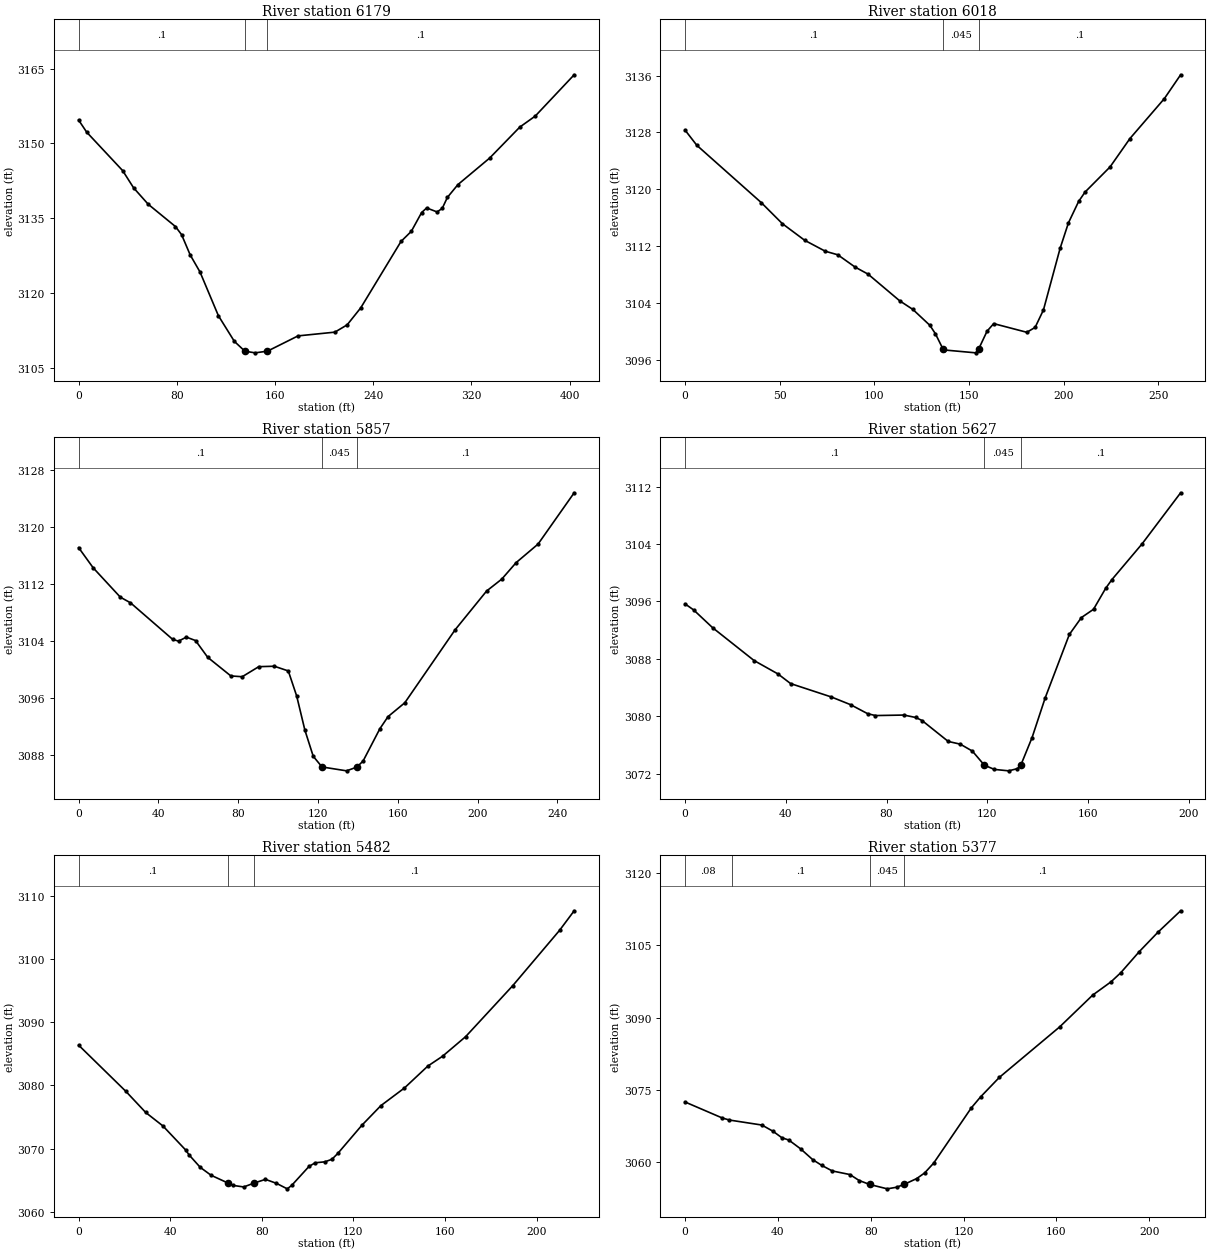
Type RM Length L Ch R = 1 ,6179    ,163.5,161.4,159.2
XS GIS Cut Line= 4
2205123.78931105574112.7770965012205154.87814332574178.011365516
2205281.02216538574272.5240367722205446.26463277574326.612908246
#Sta/Elev= 30
       0 3154.69     6.6 3152.26    35.9 3144.55    44.8  3141.1    56.7 3137.81
    78.9 3133.34    83.9 3131.71    90.9 3127.65    98.9 3124.23   113.9 3115.45
   126.9 3110.31   135.5 3108.33   143.9 3108.01   153.9 3108.35   178.8 3111.41
   208.8 3112.16   218.8 3113.62   229.9 3117.04   262.7 3130.35   271.1 3132.38
   279.5 3136.15   283.6 3137.07   292.1 3136.27   296.3 3136.99   300.5 3139.19
   309.1 3141.76   334.9 3147.07   359.5 3153.29   372.1  3155.5   403.8 3163.78
#Mann= 3, -1 ,  0
       0     0.1       0   135.5   0.045       0   153.9     0.1       0
Bank Sta=135.5,153.9
XS Rating Curve= 0 ,0
Exp/Cntr=0.3,0.1

Type RM Length L Ch R = 1 ,6018    ,164.5,160.6,162.8
XS GIS Cut Line= 3
2205058.83384294574273.8023463082205134.84809219574345.472924173
2205278.18924792574410.627994958
#Sta/Elev= 30
       0 3128.32     6.2 3126.19    40.3 3118.12    51.4 3115.17    63.2 3112.83
    74.1 3111.29    80.7 3110.79    89.8 3109.07    96.7 3108.07   113.4 3104.32
   120.4  3103.1   129.4 3100.86   132.3 3099.68   136.2 3097.59   136.7 3097.41
   153.6    3097  155.24 3097.59   159.6 3100.05   163.1 3101.11   180.6 3099.89
     185 3100.58   189.4 3103.04   198.2  3111.7   202.6 3115.28     208  3118.3
   211.4 3119.62   224.6 3123.15   235.1 3127.14   253.3 3132.76   261.9 3136.11
#Mann= 3, -1 ,  0
       0     0.1       0   136.2   0.045       0  155.24     0.1       0
Bank Sta=136.2,155.24
XS Rating Curve= 0 ,0
Exp/Cntr(USF)=0,0
Exp/Cntr=0.3,0.1

Type RM Length L Ch R = 1 ,5857    ,225.7,229.8,231.2
XS GIS Cut Line= 4
2204949.91646649574410.6998634912205038.78488541 574464.06162479
2205105.60330442574483.6321888772205157.04529373574538.400969903
#Sta/Elev= 30
       0  3117.1     7.3 3114.27    20.9 3110.16      26 3109.37    47.2 3104.23
    50.1    3104      54 3104.56    58.6 3104.08    64.7 3101.73    76.3 3099.12
      82 3099.01    90.3 3100.42    98.1 3100.48   105.1 3099.82   109.3 3096.31
   113.4 3091.54   117.6 3087.86     1223086.365   134.3 3085.82   139.5 3086.35
   142.6  3087.2     151 3091.72   155.1 3093.42   163.5 3095.36   188.7 3105.58
   204.5 3111.02   212.1 3112.69   219.3    3115   230.3  3117.6   248.4 3124.79
#Mann= 3, -1 ,  0
       0     0.1       0     122   0.045       0   139.5     0.1       0
Bank Sta=122,139.5
XS Rating Curve= 0 ,0
Exp/Cntr=0.3,0.1

Type RM Length L Ch R = 1 ,5627    ,143.4,145.5,144.3
XS GIS Cut Line= 2
2204845.38119735574596.8428163712205008.94651169574706.360461629
#Sta/Elev= 30
       0 3095.66     3.4 3094.82    10.9 3092.35    27.4 3087.76    36.9 3085.89
    41.9 3084.55    58.1 3082.68    65.7 3081.61    72.5 3080.35    75.6 3080.09
    86.9 3080.16    91.6 3079.82    94.1  3079.4   104.5 3076.48   109.3  3076.1
   114.1 3075.13  118.853073.168   122.8 3072.58   128.5 3072.38     132 3072.69
  133.323073.167   137.8 3077.02     143 3082.55   152.6  3091.4   157.4 3093.76
   162.2 3094.91     167 3097.82   169.5 3099.05   181.5 3104.04   196.8 3111.16
#Mann= 3, -1 ,  0
       0     0.1       0  118.85   0.045       0  133.32     0.1       0
Bank Sta=118.85,133.32
XS Rating Curve= 0 ,0
Exp/Cntr(USF)=0,0
Exp/Cntr=0.3,0.1

Type RM Length L Ch R = 1 ,5482    ,105.6,104.5,100.2
XS GIS Cut Line= 3
  2204775.580168574705.2400927832204875.91559334574769.908576584
2204970.37212921 574792.10141317
#Sta/Elev= 30
       0 3086.38    20.6 3079.07    29.3 3075.71    36.8 3073.58    46.7 3069.78
    48.3 3068.96    53.1 3067.02    57.8 3065.77   65.09 3064.55    67.3 3064.16
    72.1 3063.91    76.8 3064.55    81.6 3065.11    86.4 3064.48    91.1 3063.61
      93 3064.14   100.6 3067.16   103.3 3067.74   107.5 3067.89   110.6 3068.29
   113.2 3069.23   123.7 3073.69     132  3076.8   142.3  3079.6   152.5 3083.07
   158.9 3084.62     169 3087.73   189.5 3095.78     210 3104.57   216.4 3107.68
#Mann= 3, -1 ,  0
       0     0.1       0   65.09   0.045       0    76.8     0.1       0
Bank Sta=65.09,76.8
XS Rating Curve= 0 ,0
Exp/Cntr(USF)=0,0
Exp/Cntr=0.3,0.1

Type RM Length L Ch R = 1 ,5377    ,128.1,132.3,138.5
XS GIS Cut Line= 3
2204761.22729081574801.5958535472204804.29202946 574835.87882687
2204961.89571469574852.488520048
#Sta/Elev= 30
       0 3072.45      16 3069.13    19.1  3068.7    33.1 3067.66    37.9 3066.36
    41.7 3065.02    44.7 3064.54    49.8  3062.7      55 3060.46    58.9 3059.27
    63.4 3058.12      71 3057.37      75 3056.13   79.563055.303    87.1  3054.4
    91.1 3054.73   94.323055.314    99.8 3056.54   103.2  3057.7   107.1 3059.75
   123.3 3071.22   127.3 3073.51   135.4 3077.57   161.4 3088.07   175.6 3094.67
   183.5 3097.43   187.7 3099.32   195.7 3103.72   203.7 3107.73   213.5  3112.2
#Mann= 4, -1 ,  0
       0    0.08       0      20     0.1       0   79.56   0.045       0
   94.32     0.1       0
Bank Sta=79.56,94.32
XS Rating Curve= 0 ,0
Exp/Cntr(USF)=0,0
Exp/Cntr=0.3,0.1

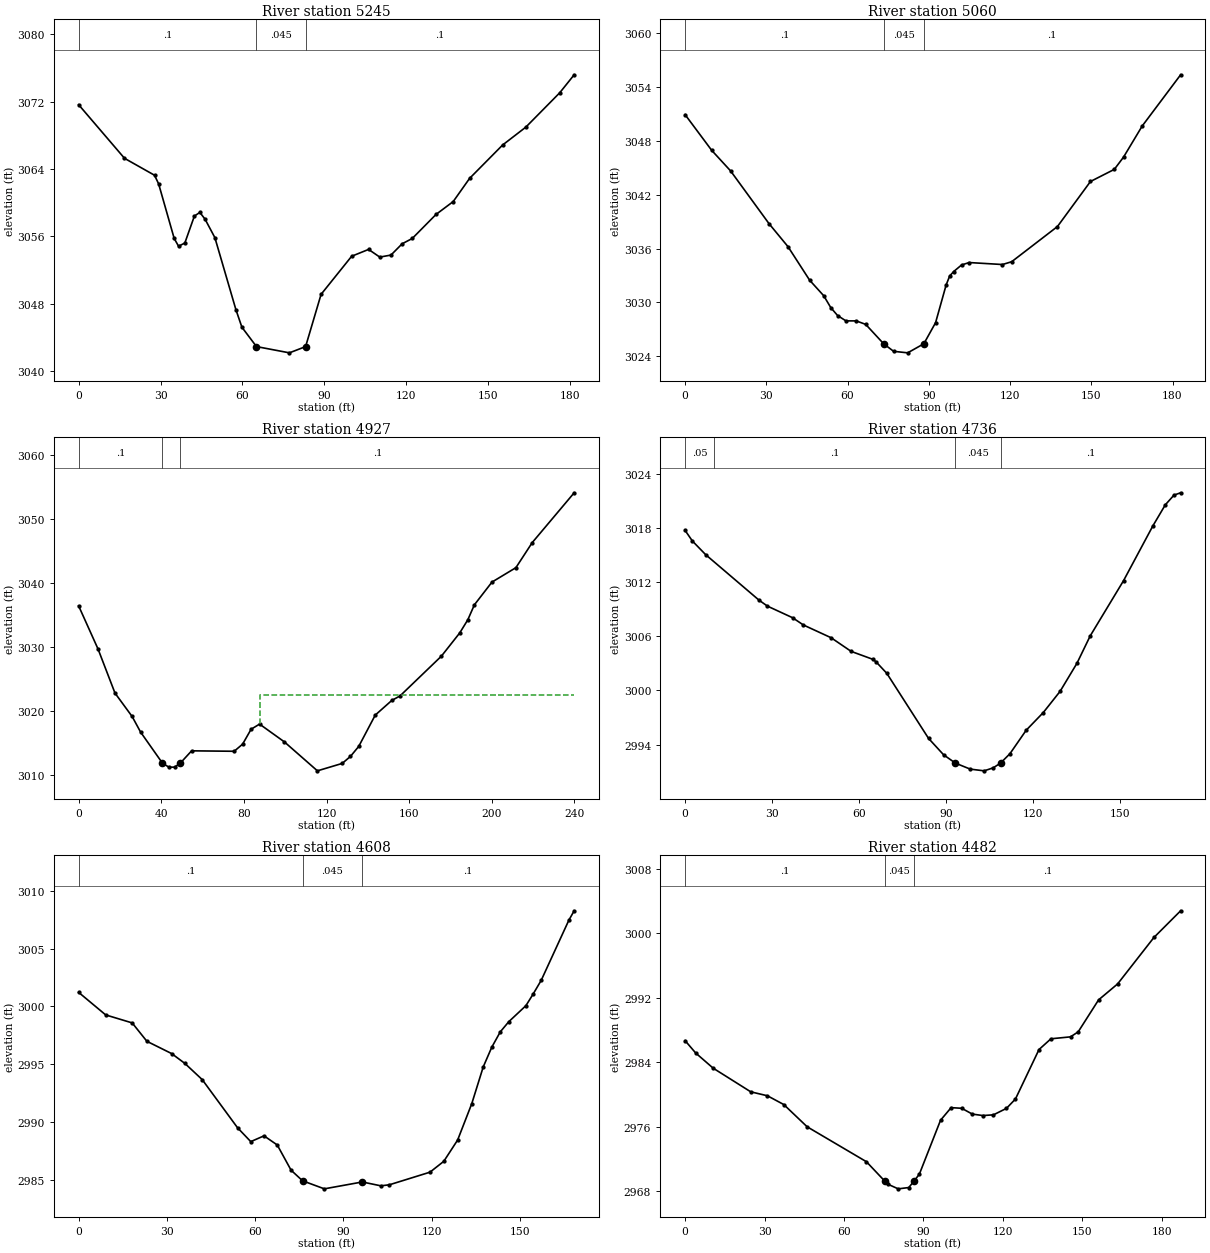
Type RM Length L Ch R = 1 ,5245    ,186.9,184.9,186.9
XS GIS Cut Line= 3
2204698.88356797574877.0373113822204772.13238266 574953.84189377
2204845.38119735574971.620732286
#Sta/Elev= 30
       0 3071.63    16.8 3065.27    27.8 3063.26    29.3 3062.24      35 3055.76
    36.6 3054.84    38.9 3055.22    42.4 3058.42    44.4 3058.85    46.3 3058.05
    49.9 3055.86    57.6 3047.32    59.8 3045.23   65.143042.932    77.2 3042.19
   83.13 3042.93    88.8 3049.13     100 3053.65   106.2 3054.46   110.3 3053.55
   114.4 3053.79   118.5 3055.13   122.2 3055.76   130.9 3058.61   137.2 3060.14
   143.2 3062.89   155.3 3066.85   163.8 3068.97   176.2 3073.04   181.5 3075.18
#Mann= 3, -1 ,  0
       0     0.1       0   65.14   0.045       0   83.13     0.1       0
Bank Sta=65.14,83.13
XS Rating Curve= 0 ,0
Exp/Cntr(USF)=0,0
Exp/Cntr=0.3,0.1

Type RM Length L Ch R = 1 ,5060    ,137.2,132.9,133.9
XS GIS Cut Line= 3
 2204604.0936748575025.6105664022204675.13633254575112.279710848
2204744.93211277575124.844545558
#Sta/Elev= 30
       0 3050.92     9.8 3046.95    16.8 3044.65      31 3038.77      38 3036.21
      46 3032.47    51.2 3030.74    53.8 3029.42    56.3 3028.54    59.4 3027.94
    63.2 3027.94    66.7 3027.55   73.313025.394      77 3024.55    82.2 3024.38
   88.173025.392    92.5 3027.74    96.4 3031.94    97.7 3032.94    99.2 3033.44
   102.1 3034.17   104.9 3034.44   117.2 3034.22   120.6 3034.53   137.5 3038.45
   149.7 3043.47   158.5 3044.82   161.9 3046.18   168.8 3049.65     183 3055.36
#Mann= 3, -1 ,  0
       0     0.1       0   73.31   0.045       0   88.17     0.1       0
Bank Sta=73.31,88.17
XS Rating Curve= 0 ,0
Exp/Cntr=0.3,0.1

Type RM Length L Ch R = 1 ,4927    ,183.6,191.3,192.5
XS GIS Cut Line= 3
2204503.03349709575121.5371078242204588.30105937 575142.26373461
2204740.40657499575145.583203131
#Sta/Elev= 30
       0 3036.42     9.4 3029.67    17.6 3022.78    25.9 3019.12      30 3016.68
   40.54 3011.84    43.7 3011.19    46.5  3011.2    49.3 3011.85    54.7 3013.75
    75.3 3013.68    79.4  3014.8    83.5 3017.13    87.6 3017.93    99.6 3015.15
   115.6 3010.62   127.6 3011.78   131.6 3012.88   135.6 3014.44   143.6 3019.34
   151.6 3021.63   155.6 3022.34   175.6 3028.55   184.5 3032.19   188.4 3034.24
   191.6 3036.59   200.1 3040.14   211.7  3042.4   219.6 3046.32   239.9 3054.11
#Mann= 3, -1 ,  0
       0     0.1       0   40.54   0.045       0    49.3     0.1       0
#XS Ineff= 2 , 0
                            87.8         3022.42
Permanent Ineff=
       F       F
Bank Sta=40.54,49.3
XS Rating Curve= 0 ,0
Exp/Cntr(USF)=0,0
Exp/Cntr=0.3,0.1

Type RM Length L Ch R = 1 ,4736    ,123.2,127.6,132.4
XS GIS Cut Line= 2
2204474.22446617575251.7264839732204616.58732864575346.486000572
#Sta/Elev= 30
       0 3017.74     2.5 3016.57     7.1 3015.05    25.5 3010.01    28.4 3009.35
    37.1 3008.06    40.8 3007.26    50.4 3005.84    57.3 3004.33    64.8 3003.45
    65.9 3003.17    69.6  3001.9      84 2994.69    89.2 2992.87   93.272991.946
    98.4 2991.28   103.2 2991.09   106.3 2991.42  108.842991.945   112.1 2992.99
   117.7 2995.59   123.6 2997.55   129.4  2999.9   135.2    3003   139.8 3006.05
   151.3 3012.17   161.4 3018.23   165.7 3020.57   168.7 3021.65     171 3021.91
#Mann= 4, -1 ,  0
       0    0.05       0      10     0.1       0   93.27   0.045       0
  108.84     0.1       0
Bank Sta=93.27,108.84
XS Rating Curve= 0 ,0
Exp/Cntr=0.3,0.1

Type RM Length L Ch R = 1 ,4608    ,132.2,126,120.6
XS GIS Cut Line= 3
2204457.18545356 575340.974977992204487.96145903575401.670260692
2204541.23912049575486.658905035
#Sta/Elev= 30
       0 3001.21     9.2 2999.26    18.2 2998.57    23.2 2996.98    31.6 2995.92
    36.1 2995.07      42 2993.67      54 2989.51    58.5 2988.31      63 2988.81
    67.5 2988.02    72.2 2985.84    76.12984.925    83.5 2984.23    96.42984.824
   102.7 2984.49   105.6 2984.58   119.4 2985.67   124.1 2986.61   128.8 2988.45
   133.6 2991.59   137.5 2994.77   140.4 2996.47   143.3  2997.8   146.2 2998.68
     152 3000.06   154.4 3001.04   157.2 3002.25   166.6 3007.45   168.4 3008.26
#Mann= 3, -1 ,  0
       0     0.1       0    76.1   0.045       0    96.4     0.1       0
Bank Sta=76.1,96.4
XS Rating Curve= 0 ,0
Exp/Cntr(USF)=0,0
Exp/Cntr=0.3,0.1

Type RM Length L Ch R = 1 ,4482    ,196.1,206.7,218.7
XS GIS Cut Line= 4
2204340.33867673575462.1188312782204369.73371053575497.579506966
 2204446.7207038575500.3790339942204503.64442004575529.774067789
#Sta/Elev= 30
       0 2986.68       4 2985.15    10.6 2983.27    24.8 2980.34    31.1 2979.85
    37.3 2978.76    46.1 2976.01    68.5 2971.68   75.352969.304    76.5 2968.91
    80.5 2968.32    84.5 2968.48   86.532969.303    88.5 2970.14    96.5 2976.82
   100.5 2978.38   104.5  2978.3   108.5 2977.58   112.5  2977.4   116.5 2977.49
   121.4 2978.29   124.8 2979.45   133.7 2985.58   138.2 2986.91   145.6 2987.15
   148.5 2987.77   156.2 2991.73   163.4 2993.71   177.1 2999.46   187.2 3002.77
#Mann= 3, -1 ,  0
       0     0.1       0   75.35   0.045       0   86.53     0.1       0
Bank Sta=75.35,86.53
XS Rating Curve= 0 ,0
Exp/Cntr(USF)=0,0
Exp/Cntr=0.3,0.1

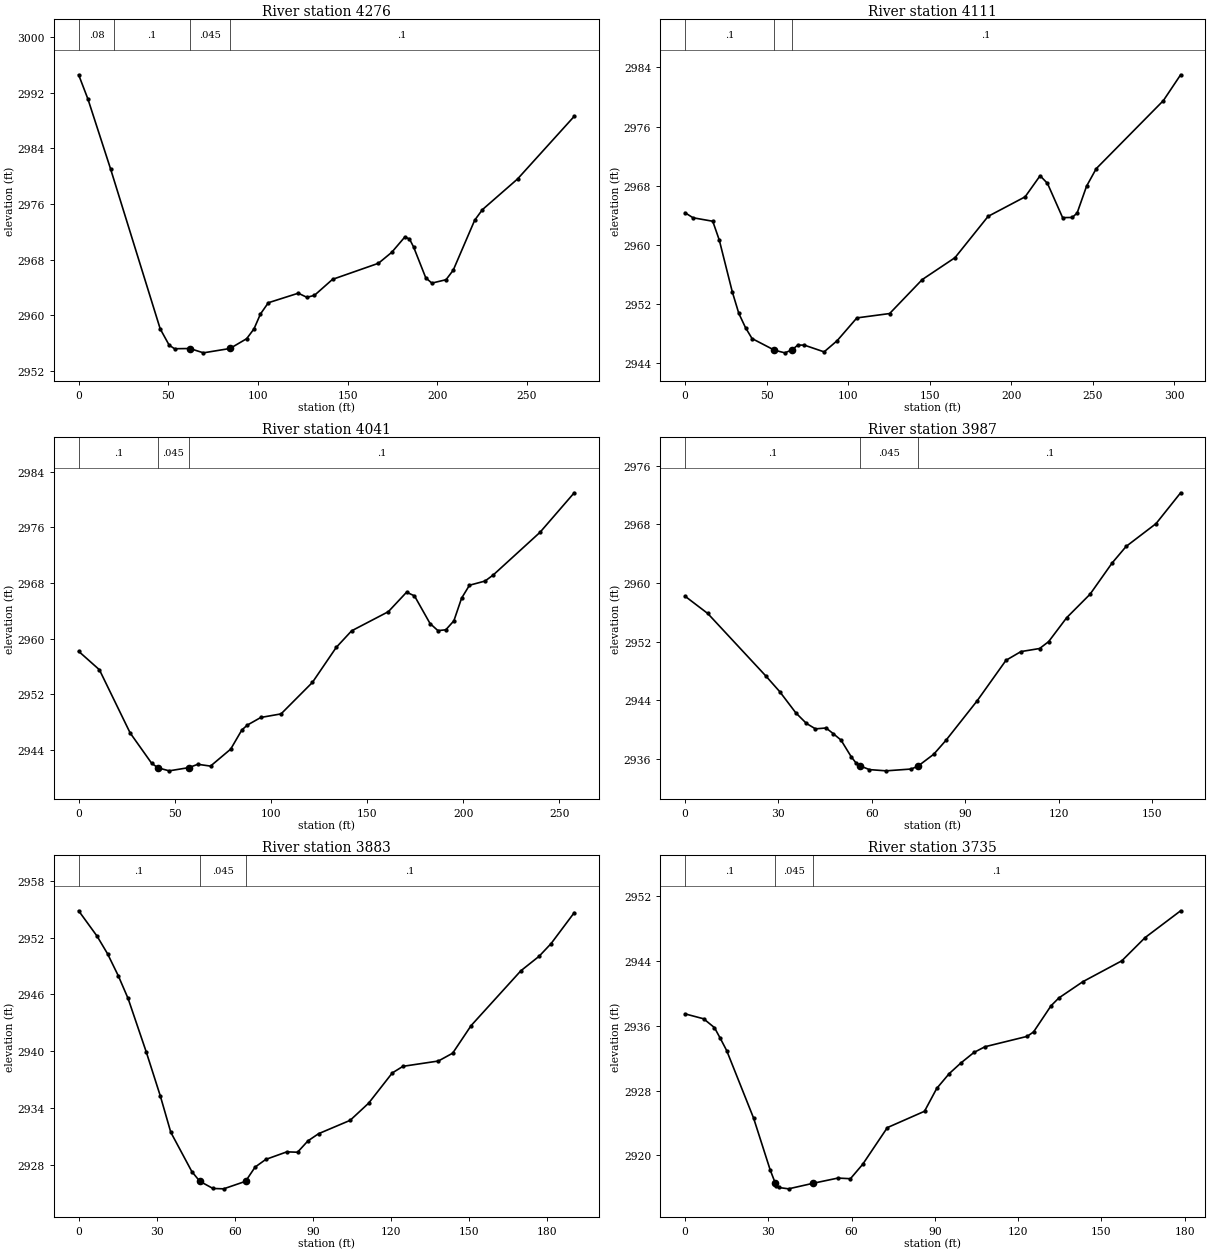
Type RM Length L Ch R = 1 ,4276    ,174,164.6,145.7
XS GIS Cut Line= 4
2204258.49771243575487.979438648 2204246.8151898575598.679541198
 2204308.0061386 575638.493672612204398.43677402575656.053019292
#Sta/Elev= 30
       0 2994.59     5.2 2991.09    17.8 2981.07    45.5 2958.07    50.5 2955.73
    53.5 2955.22   62.012955.252    69.6 2954.63   84.392955.254    93.7 2956.66
    97.8 2958.07   101.4 2960.21   105.8 2961.83   122.5  2963.2   127.3 2962.61
   131.5 2962.89   141.6 2965.19   167.2  2967.5   174.6 2969.07   181.9 2971.27
   184.5    2971   186.8 2969.85   193.6 2965.41     197 2964.65   204.9 2965.14
   208.9  2966.5   220.9  2973.7   225.2 2975.21   244.8 2979.62   276.4 2988.62
#Mann= 4, -1 ,  0
       0    0.08       0      20     0.1       0   62.01   0.045       0
   84.39     0.1       0
Bank Sta=62.01,84.39
XS Rating Curve= 0 ,0
Exp/Cntr(USF)=0,0
Exp/Cntr=0.3,0.1

Type RM Length L Ch R = 1 ,4111    ,75.2,70,63.2
XS GIS Cut Line= 3
2204083.27266162575652.1433582622204268.37418852575634.752505627
2204371.42033656575692.355942418
#Sta/Elev= 30
       0 2964.36     4.9 2963.68      17 2963.21      21 2960.67      29 2953.66
      33 2950.75    37.1 2948.83    41.1 2947.36    54.82945.792    61.2 2945.43
    65.5 2945.82    69.2 2946.48    73.2 2946.47    85.3 2945.56    93.3 2947.07
   105.4 2950.15   125.5 2950.74   145.5 2955.33   165.6 2958.29   185.9 2963.87
   208.6 2966.51   217.8 2969.36   222.3 2968.33   231.6  2963.7   237.5 2963.72
   240.5 2964.32   246.3 2967.95   252.2 2970.31   293.4 2979.51     304    2983
#Mann= 3, -1 ,  0
       0     0.1       0    54.8   0.045       0    65.5     0.1       0
Bank Sta=54.8,65.5
XS Rating Curve= 0 ,0
Exp/Cntr(USF)=0,0
Exp/Cntr=0.3,0.1

Type RM Length L Ch R = 1 ,4041    ,43.4,54,70.2
XS GIS Cut Line= 4
 2204137.3831903575710.5768878792204176.95707073575708.214268152
2204205.89916238575661.2572010752204365.67132143575693.743222323
#Sta/Elev= 30
       0  2958.2    10.8 2955.55    26.8 2946.47      38 2942.11    41.3 2941.46
    47.1 2941.03    57.3 2941.49      62 2941.97    68.6 2941.71    79.1 2944.15
    84.9  2946.9    87.8 2947.61    94.8  2948.7   105.3 2949.21   121.6 2953.73
     134 2958.76     142 2961.14   161.1 2963.89   170.6 2966.69   174.7 2966.16
   182.8 2962.19   186.9 2961.17     191 2961.29   195.2 2962.58   199.2 2965.83
   203.3 2967.69   211.4 2968.29   215.7 2969.17     240 2975.29   257.8 2980.97
#Mann= 3, -1 ,  0
       0     0.1       0    41.3   0.045       0    57.3     0.1       0
Bank Sta=41.3,57.3
XS Rating Curve= 0 ,0
Exp/Cntr(USF)=0,0
Exp/Cntr=0.3,0.1

Type RM Length L Ch R = 1 ,3987    ,99.9,104.1,114.4
XS GIS Cut Line= 2
2204134.58877012575712.6405825042204266.75071411575801.431864408
#Sta/Elev= 30
       0 2958.19     7.3 2955.83      26 2947.28    30.4 2945.17    35.6 2942.26
      39 2940.82    41.9 2940.08    45.3  2940.2    47.6 2939.43    50.1 2938.55
    53.4 2936.26    54.9 2935.44    56.3 2935.02    59.2 2934.52    64.6 2934.35
    72.7  2934.6   74.88 2935.01    79.9 2936.62    83.8 2938.51    93.8 2943.89
   103.1 2949.44   107.9 2950.63   113.9 2951.05   116.8 2951.99   122.6 2955.26
   130.1 2958.46   137.2 2962.73   141.7 2964.99   151.3  2968.1   159.2 2972.31
#Mann= 3, -1 ,  0
       0     0.1       0    56.3   0.045       0   74.88     0.1       0
Bank Sta=56.3,74.88
XS Rating Curve= 0 ,0
Exp/Cntr(USF)=0,0
Exp/Cntr=0.3,0.1

Type RM Length L Ch R = 1 ,3883    ,153.9,148.2,138.8
XS GIS Cut Line= 3
2204081.36661968575730.1972908352204102.52640251575861.186422652
2204142.32694641575903.002183963
#Sta/Elev= 30
       0 2954.84     7.1 2952.15    11.1  2950.3    15.2 2947.99      19 2945.57
      26  2939.9    31.4 2935.25    35.4 2931.43    43.5 2927.27   46.54 2926.25
    51.6 2925.49    55.7 2925.45   64.132926.245    67.8 2927.75    71.9 2928.56
      80 2929.36    84.1 2929.32    88.1 2930.52    92.2 2931.28   104.3 2932.69
   111.4  2934.5   120.5  2937.7   124.6  2938.4   138.2 2938.96   143.7 2939.79
   150.8 2942.71   169.9  2948.5   176.9 2950.03   181.5 2951.37   190.4 2954.64
#Mann= 3, -1 ,  0
       0     0.1       0   46.54   0.045       0   64.13     0.1       0
Bank Sta=46.54,64.13
XS Rating Curve= 0 ,0
Exp/Cntr(USF)=0,0
Exp/Cntr=0.3,0.1

Type RM Length L Ch R = 1 ,3735    ,116.5,121.5,123.7
XS GIS Cut Line= 3
2203946.69095409575849.6424564012204058.44162146575904.365721353
2204097.61195848575941.807955267
#Sta/Elev= 30
       0 2937.47     6.7 2936.86    10.6 2935.77    12.7 2934.45      15 2932.94
    24.7  2924.6    30.7 2918.18   32.54 2916.55    32.8  2916.2    33.7 2916.03
    37.3 2915.86    46.2 2916.55    55.1 2917.19    59.6 2917.11      64 2918.88
    72.9 2923.42    86.3 2925.44    90.7 2928.26    95.2 2930.09    99.4  2931.4
   104.1  2932.7   108.1 2933.41   123.3 2934.69   125.6 2935.24   131.9 2938.47
   134.7 2939.43   143.4 2941.45   157.4 2944.02   165.8 2946.89   178.6  2950.2
#Mann= 3, -1 ,  0
       0     0.1       0   32.54   0.045       0    46.2     0.1       0
Bank Sta=32.54,46.2
XS Rating Curve= 0 ,0
Exp/Cntr(USF)=0,0
Exp/Cntr=0.3,0.1

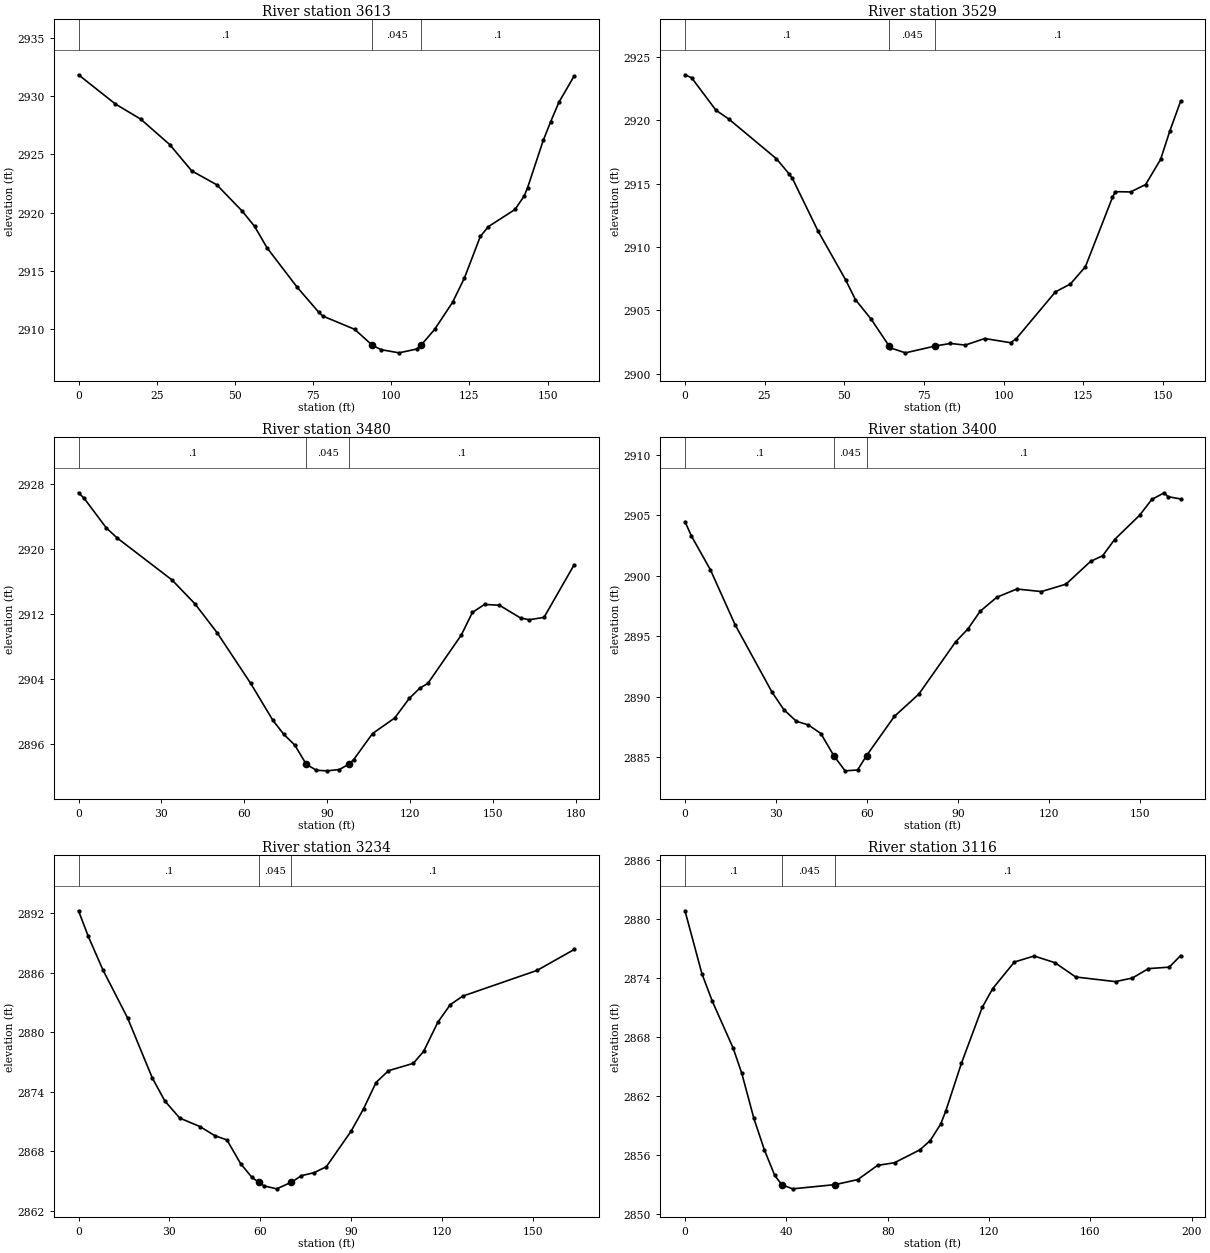
Type RM Length L Ch R = 1 ,3613    ,84.3,84.6,87.3
XS GIS Cut Line= 3
2203890.75165845575873.4867492182203900.99226943575942.610873368
 2203954.7554771576013.015073891
#Sta/Elev= 30
       0 2931.83    11.8 2929.32    19.9 2928.02    29.2 2925.83    36.2 2923.58
    44.2 2922.39    52.3 2920.14    56.3 2918.82    60.3 2916.97    69.9  2913.6
    76.8 2911.45    78.1 2911.12    88.3 2909.98      94  2908.6    96.8 2908.23
   102.5 2907.96   108.2 2908.29  109.472908.595   113.9 2909.98   119.6 2912.29
   123.4 2914.38   128.5 2917.96   131.1  2918.8   139.6 2920.27   142.5 2921.42
   143.6 2922.13   148.6 2926.19     151 2927.81   153.6 2929.46   158.5 2931.73
#Mann= 3, -1 ,  0
       0     0.1       0      94   0.045       0  109.47     0.1       0
Bank Sta=94,109.47
XS Rating Curve= 0 ,0
Exp/Cntr(USF)=0,0
Exp/Cntr=0.3,0.1

Type RM Length L Ch R = 1 ,3529    ,42.4,49,50.1
XS GIS Cut Line= 3
2203824.53062342575907.5004847242203825.53823212575953.346680861
2203883.47573273576046.550486193
#Sta/Elev= 30
       0 2923.58     2.1 2923.34     9.7 2920.79    13.7  2920.1    28.7 2916.96
    32.6 2915.79    33.7 2915.42    41.7 2911.29    50.4 2907.42    53.5 2905.85
    58.4 2904.32   64.08 2902.19    64.5 2902.04    69.2 2901.65    78.6 2902.19
    83.3 2902.39      88 2902.26    94.1 2902.78   102.2 2902.45   103.9 2902.74
   116.3 2906.46     121 2907.08   125.7 2908.44   134.2 2913.91   135.1 2914.36
   139.9 2914.34   144.6 2914.92   149.3  2916.9   152.2 2919.14   155.6  2921.5
#Mann= 3, -1 ,  0
       0     0.1       0   64.08   0.045       0    78.6     0.1       0
Bank Sta=64.08,78.6
XS Rating Curve= 0 ,0
Exp/Cntr(USF)=0,0
Exp/Cntr=0.3,0.1

Type RM Length L Ch R = 1 ,3480    ,80.7,79.4,81.7
XS GIS Cut Line= 3
2203789.98827653575899.1836035472203800.75208378 576043.94282362
2203823.41819006576069.343052347
#Sta/Elev= 30
       0 2926.93       2 2926.27      10 2922.62      14 2921.36    33.8  2916.2
    42.1 2913.26    50.1 2909.71    62.2 2903.49    70.2 2898.96    74.2  2897.2
    78.2 2895.87   82.332893.514      86 2892.77    89.8  2892.7    94.3 2892.86
   97.742893.514    99.5 2894.09   106.3 2897.29   114.3  2899.2   119.6 2901.62
   123.4 2902.88   126.3 2903.46   138.4 2909.42   142.4  2912.2   146.8 2913.19
   152.2 2913.08   159.8 2911.52   162.9  2911.3   168.3 2911.59   179.2 2918.07
#Mann= 3, -1 ,  0
       0     0.1       0   82.33   0.045       0   97.74     0.1       0
Bank Sta=82.33,97.74
XS Rating Curve= 0 ,0
Exp/Cntr=0.3,0.1

Type RM Length L Ch R = 1 ,3400    ,165.5,166.5,161.6
XS GIS Cut Line= 2
2203728.48519242575956.8866335172203704.84992647 576118.60161107
#Sta/Elev= 30
       0 2904.48     2.1  2903.3     8.4 2900.49    16.5 2895.97    28.7 2890.39
    32.6 2888.94    36.7 2887.99    40.7 2887.68    44.8 2886.97   49.162885.102
    52.8 2883.89    56.9 2883.96   59.852885.143      69 2888.38    77.1 2890.23
    89.2 2894.54    93.3 2895.62    97.3 2897.07   102.8 2898.23   109.4 2898.91
   117.5  2898.7   125.6 2899.31   133.7 2901.19   137.7 2901.66   141.6 2902.99
   149.9 2905.01   153.9 2906.31     158 2906.86   159.2 2906.54   163.4 2906.35
#Mann= 3, -1 ,  0
       0     0.1       0   49.16   0.045       0   59.85     0.1       0
Bank Sta=49.16,59.85
XS Rating Curve= 0 ,0
Exp/Cntr(USF)=0,0
Exp/Cntr=0.3,0.1

Type RM Length L Ch R = 1 ,3234    ,118.3,118.1,117.9
XS GIS Cut Line= 2
2203568.13157813575997.3611532812203603.60328453576157.066802989
#Sta/Elev= 30
       0 2892.23     3.2 2889.67       8 2886.31    16.2 2881.43    24.4 2875.36
    28.5 2873.07    33.4 2871.35    40.1 2870.49    44.9 2869.59      49 2869.14
    53.5 2866.76    57.2 2865.39   59.49 2864.88    61.3 2864.51    65.4 2864.22
    70.3 2864.89    73.6 2865.55    77.7 2865.84    81.8 2866.45      90 2870.04
    94.1 2872.29    98.2 2874.93   102.3 2876.12   110.5 2876.86   113.9 2878.06
   118.6    2881   122.7 2882.77   126.8 2883.63   151.4 2886.23   163.6 2888.33
#Mann= 3, -1 ,  0
       0     0.1       0   59.49   0.045       0    70.3     0.1       0
Bank Sta=59.49,70.3
XS Rating Curve= 0 ,0
Exp/Cntr=0.3,0.1

Type RM Length L Ch R = 1 ,3116    ,194.2,191.1,185.9
XS GIS Cut Line= 2
2203456.05765331576034.6342188792203498.35233975576225.582288528
#Sta/Elev= 30
       0  2880.8     6.7  2874.4    10.8 2871.61      19 2866.87    22.4 2864.32
    27.2 2859.72    31.3 2856.56    35.4 2853.95   38.24 2852.99    42.5 2852.58
    59.3 2853.01    68.2 2853.52      76 2854.96    82.7 2855.23    92.7 2856.54
    96.8 2857.48   100.9 2859.15   102.9 2860.46   109.1 2865.33   117.3 2870.99
   121.4 2872.89     130  2875.6   137.8 2876.21     146 2875.53   154.2 2874.08
   169.9 2873.61   176.6 2873.98   182.9 2874.93   191.1 2875.08   195.6 2876.25
#Mann= 3, -1 ,  0
       0     0.1       0   38.24   0.045       0    59.3     0.1       0
Bank Sta=38.24,59.3
XS Rating Curve= 0 ,0
Exp/Cntr(USF)=0,0
Exp/Cntr=0.3,0.1

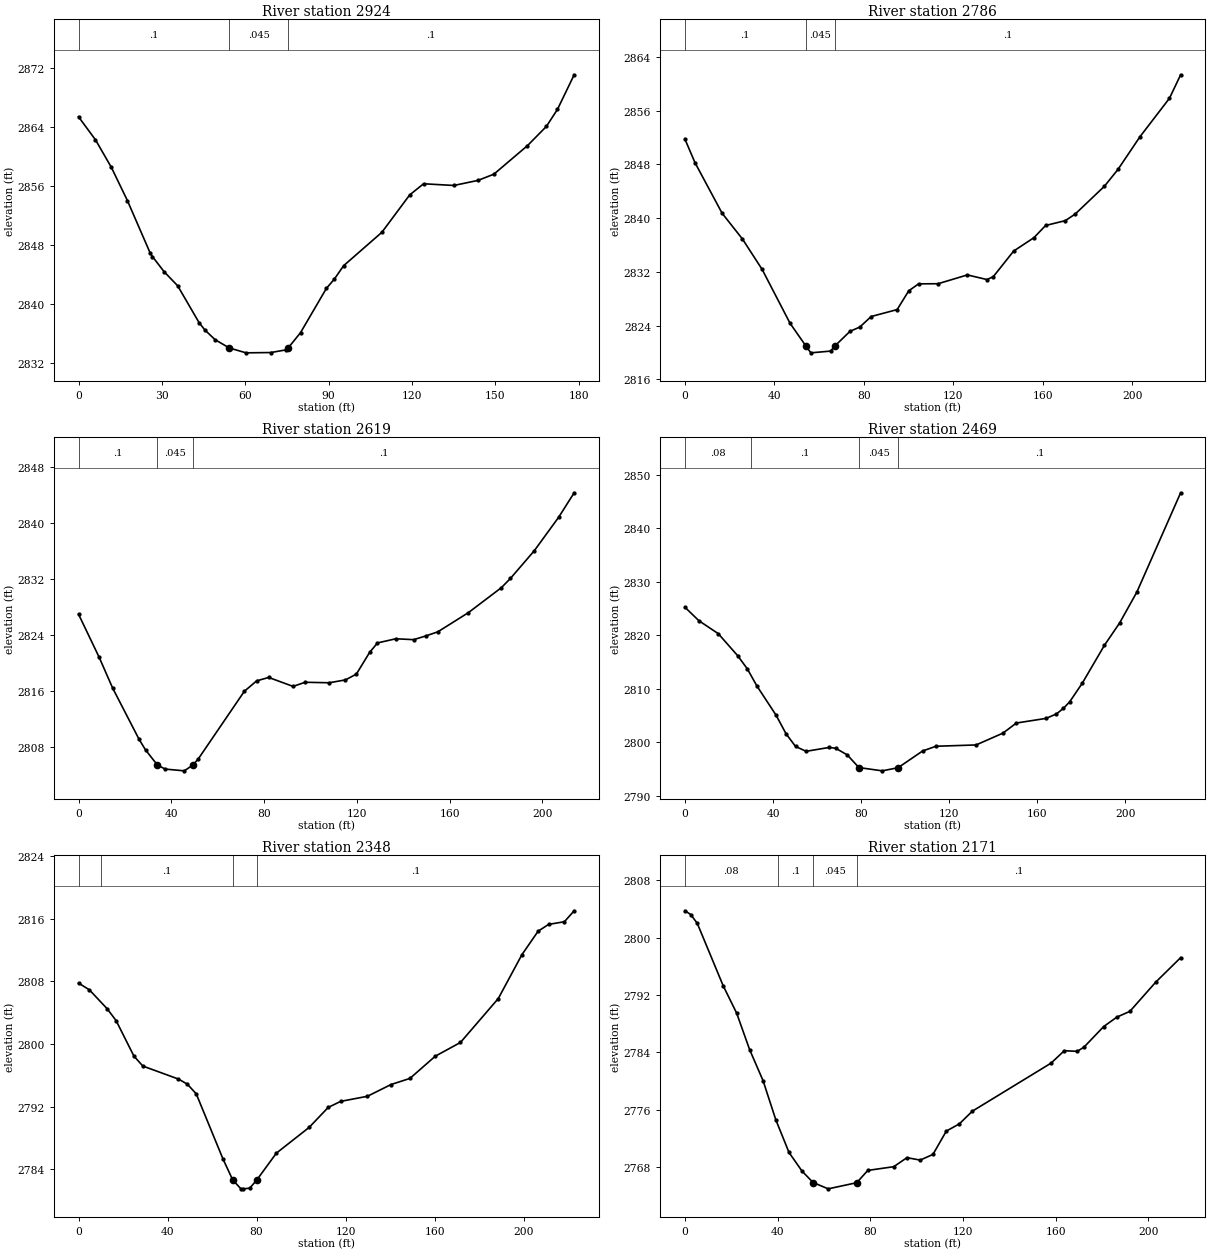
Type RM Length L Ch R = 1 ,2924    ,135.7,138.7,140.4
XS GIS Cut Line= 2
2203300.70960561  576156.15113642203404.39579183576301.311797114
#Sta/Elev= 30
       0 2865.39     6.1 2862.27    11.8 2858.55    17.6 2854.03    25.8 2846.92
    26.6 2846.45    30.8  2844.4    35.7 2842.48    43.4 2837.49    45.5 2836.49
    49.1  2835.2   54.262834.061    60.3  2833.4    69.2 2833.44    74.8 2833.81
   75.45 2834.06    79.9 2836.13    89.2 2842.12    92.1  2843.4    95.4  2845.2
   109.2 2849.74   119.2  2854.8   124.2 2856.31   135.1 2856.08   143.8 2856.77
   149.5 2857.61   161.6 2861.48   168.4 2864.08   172.4  2866.4   178.4 2871.08
#Mann= 3, -1 ,  0
       0     0.1       0   54.26   0.045       0   75.45     0.1       0
Bank Sta=54.26,75.45
XS Rating Curve= 0 ,0
Exp/Cntr(USF)=0,0
Exp/Cntr=0.3,0.1

Type RM Length L Ch R = 1 ,2786    ,168.5,166.9,164.2
XS GIS Cut Line= 2
2203189.71224846576209.6805205292203279.55390266 576412.40015051
#Sta/Elev= 30
       0 2851.73     4.5 2848.23    16.6 2840.72    25.7 2836.88    34.5 2832.36
      47 2824.33   53.952821.013    56.3 2819.93    65.1 2820.19   67.252821.016
    73.8 2823.13    78.2 2823.77    83.3 2825.34    94.9 2826.37   100.1 2829.17
   104.5  2830.2   113.2 2830.22   126.3 2831.53   135.1 2830.84   137.9 2831.27
     147 2835.08   156.1 2837.08   161.3 2838.89   170.1 2839.61   174.5 2840.58
   187.6 2844.73   193.7 2847.25   203.5  2852.1   216.7 2857.83   221.7 2861.33
#Mann= 3, -1 ,  0
       0     0.1       0   53.95   0.045       0   67.25     0.1       0
Bank Sta=53.95,67.25
XS Rating Curve= 0 ,0
Exp/Cntr(USF)=0,0
Exp/Cntr=0.3,0.1

Type RM Length L Ch R = 1 ,2619    ,149.1,150.5,149.8
XS GIS Cut Line= 2
2203038.49536406576290.1485164882203175.30670098   576454.324931
#Sta/Elev= 30
       0 2826.97     8.9  2820.8    14.7  2816.4    26.1 2809.06    28.9 2807.53
   34.052805.363    37.4 2804.79    45.6 2804.54    49.32805.363    51.6 2806.23
    71.5 2815.93    76.8 2817.42      82 2817.91    92.5 2816.63    97.7 2817.22
   108.1 2817.15   115.1 2817.56   119.8 2818.39   125.5 2821.49   128.9 2822.85
   136.8 2823.45   144.5 2823.32   149.7 2823.85   154.9 2824.44   168.1 2827.19
   182.3 2830.76   186.2 2832.08   196.5 2836.05     207 2840.84   213.7 2844.35
#Mann= 3, -1 ,  0
       0     0.1       0   34.05   0.045       0    49.3     0.1       0
Bank Sta=34.05,49.3
XS Rating Curve= 0 ,0
Exp/Cntr=0.3,0.1

Type RM Length L Ch R = 1 ,2469    ,113.8,120.7,126.4
XS GIS Cut Line= 3
2202953.09571512576371.4364583712202979.93762204576430.631769583
 2203085.2375984576551.182973052
#Sta/Elev= 30
       0 2825.25     6.3 2822.74    15.1 2820.32    23.9 2816.21    28.3 2813.74
    32.7 2810.51    41.4 2805.05    45.9 2801.59    50.2 2799.23      55 2798.31
    65.4 2799.03    68.4 2798.89    73.7 2797.64      79 2795.27    89.6 2794.66
    96.82795.247   107.9 2798.37     114 2799.26   132.2  2799.5   144.4 2801.71
   150.5  2803.6     164 2804.47   168.7  2805.3   171.9 2806.36   174.7 2807.56
   180.4 2811.03   190.5 2818.14   197.4 2822.32   205.2 2828.07   225.1 2846.66
#Mann= 4, -1 ,  0
       0    0.08       0      30     0.1       0      79   0.045       0
    96.8     0.1       0
Bank Sta=79,96.8
XS Rating Curve= 0 ,0
Exp/Cntr(USF)=0,0
Exp/Cntr=0.3,0.1

Type RM Length L Ch R = 1 ,2348    ,183.8,177.1,170.7
XS GIS Cut Line= 3
2202880.44135846576388.3248072942202875.96109115576488.170764399
2202959.16605541576578.416148706
#Sta/Elev= 30
       0 2807.78     4.9 2806.91    12.9 2804.49    16.9 2802.98    24.9 2798.45
    28.9 2797.18    44.9 2795.52    48.9 2794.87    52.9 2793.63    64.9 2785.32
   69.292782.637    72.9 2781.52    73.9  2781.5    76.9 2781.58   80.122782.639
    88.9 2786.06   103.6 2789.34   112.2  2791.9   117.8 2792.67   129.8 2793.32
   140.4 2794.82   148.9  2795.6   160.3 2798.44   171.6 2800.19   188.6  2805.8
   199.2 2811.39   206.5  2814.4   211.2 2815.27   218.3 2815.61   222.7 2817.01
#Mann= 4, -1 ,  0
       0    0.08       0      10     0.1       0   69.29   0.045       0
   80.12     0.1       0
Bank Sta=69.29,80.12
XS Rating Curve= 0 ,0
Exp/Cntr(USF)=0,0
Exp/Cntr=0.3,0.1

Type RM Length L Ch R = 1 ,2171    ,84.5,83.7,83.1
XS GIS Cut Line= 2
2202664.48411624576465.3836901632202815.75596134576616.655535263
#Sta/Elev= 30
       0 2803.76     2.5 2803.23     5.3 2802.01    16.5 2793.29    22.3 2789.48
    27.9 2784.39    33.7 2780.06    39.2  2774.6    44.9 2770.04    50.5 2767.45
   55.282765.852    61.8 2764.97   74.122765.826    78.9 2767.54    90.1 2768.06
    95.8 2769.32   101.5 2768.98     107 2769.77   112.8 2773.03   118.4 2774.03
     124  2775.8     158 2782.51   163.7 2784.24   169.3 2784.15   172.2 2784.74
   180.7 2787.61   186.4 2788.93     192 2789.73   203.2 2793.82   213.9 2797.22
#Mann= 4, -1 ,  0
       0    0.08       0      40     0.1       0   55.28   0.045       0
   74.12     0.1       0
Bank Sta=55.28,74.12
XS Rating Curve= 0 ,0
Exp/Cntr(USF)=0,0
Exp/Cntr=0.3,0.1