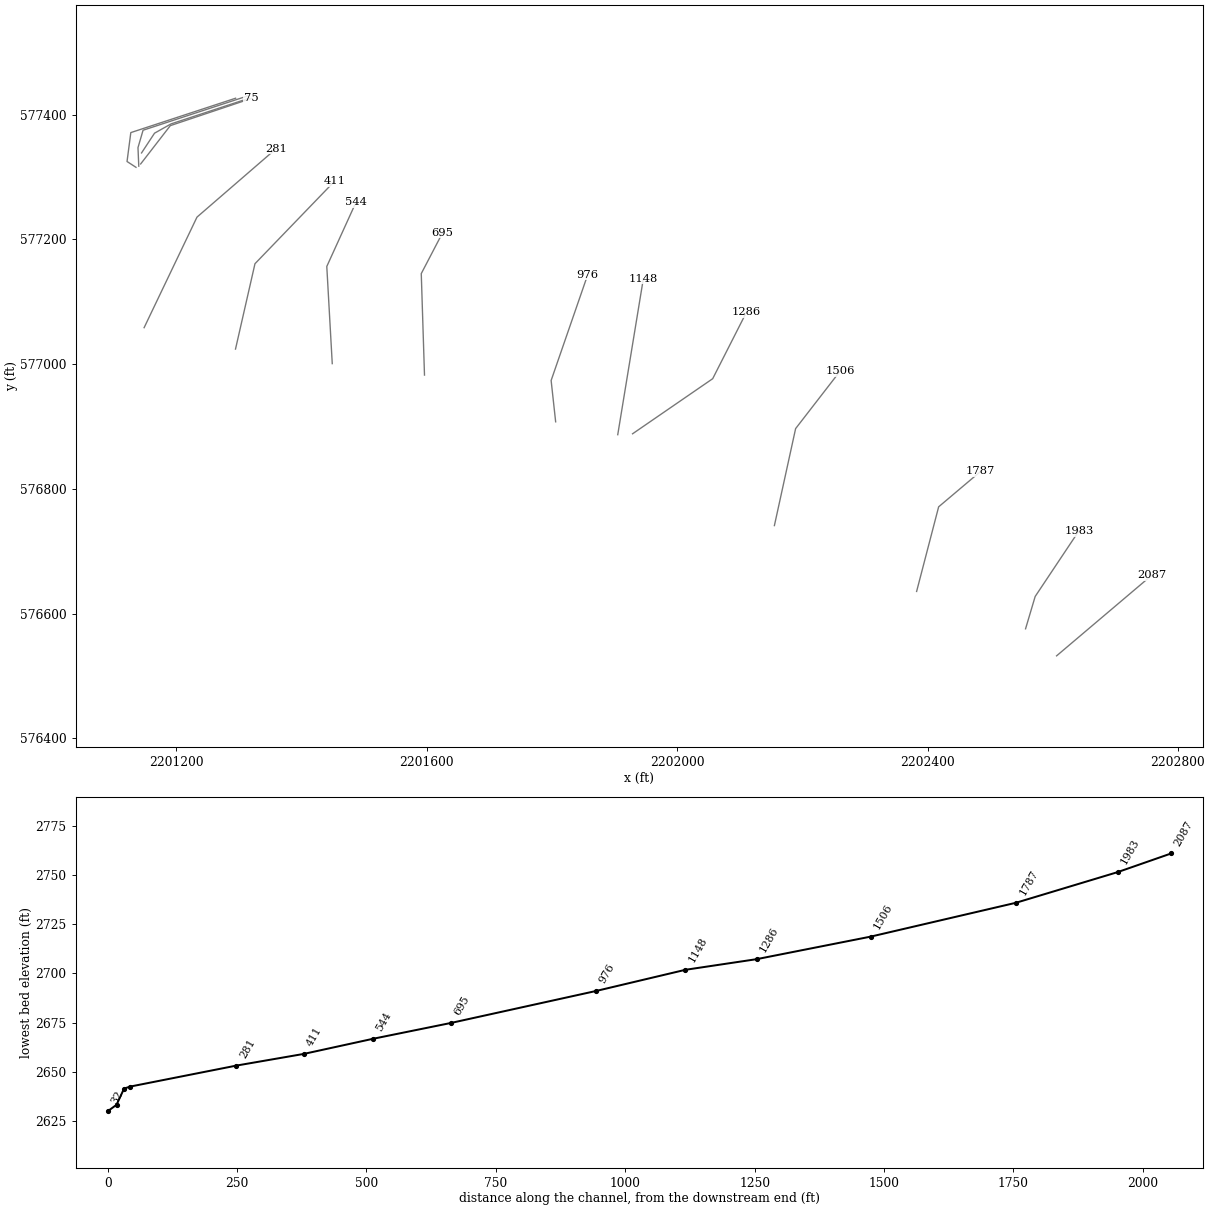
HEC-RAS study FLINTRN.prj: FLINTRN

--- FLINTRN.g01 (geometry) --- (continued)

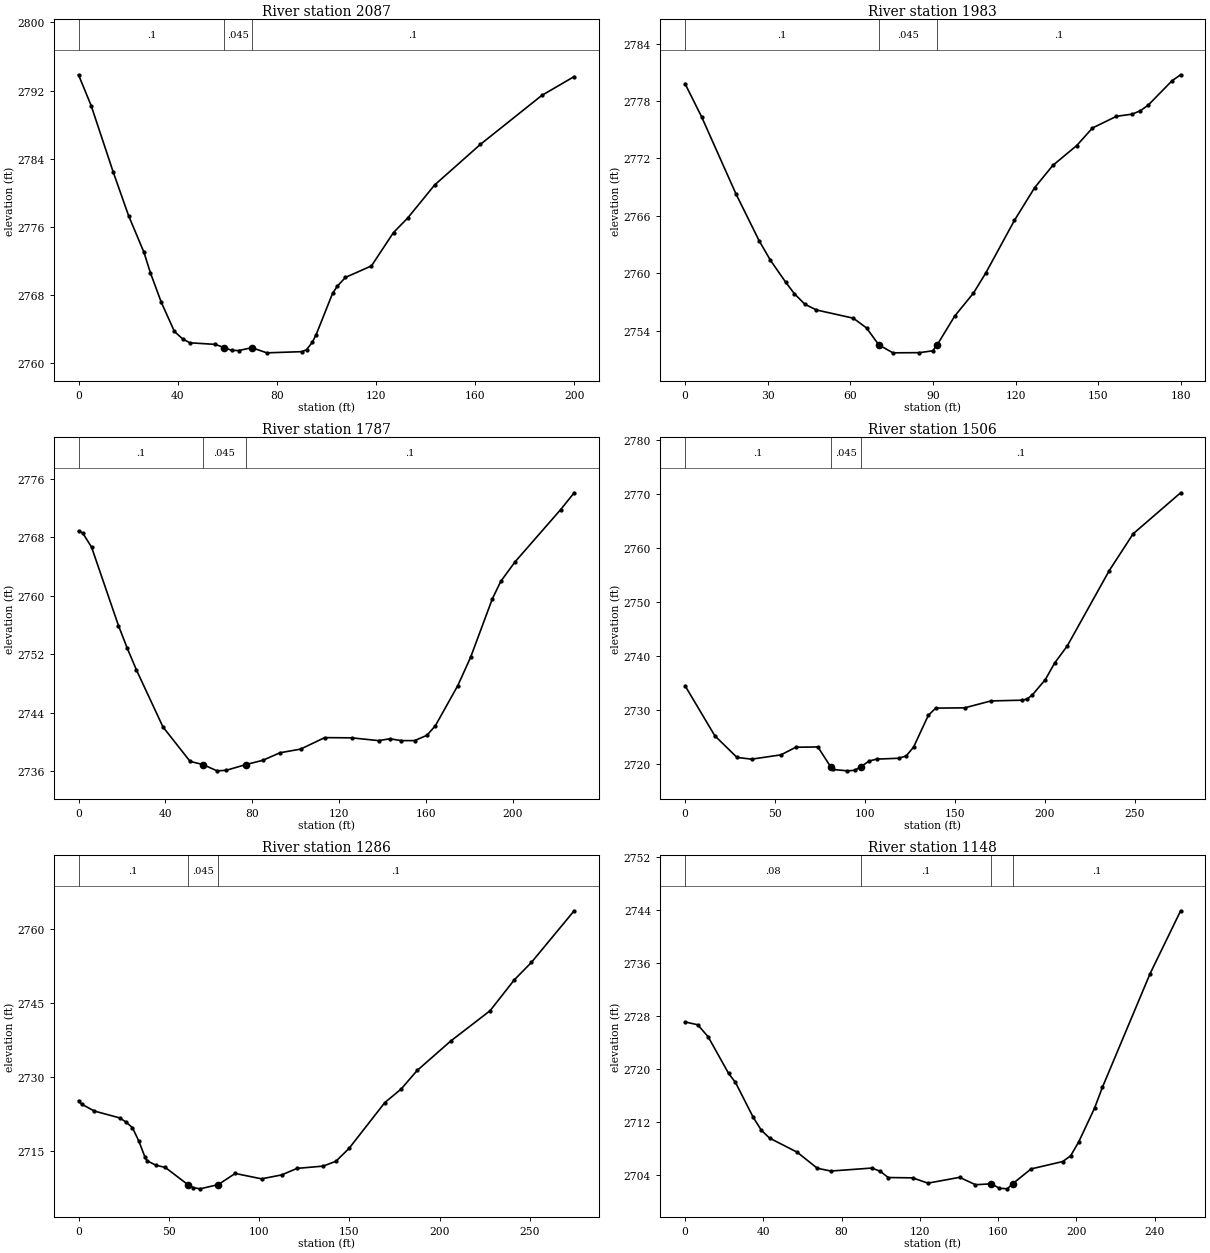
Type RM Length L Ch R = 1 ,2087    ,101.2,103.6,106.9
XS GIS Cut Line= 2
2202606.11131855576532.1038706452202758.46605283576661.605394785
#Sta/Elev= 30
       0 2793.86     5.1 2790.24      14 2782.45    20.2 2777.33    26.4 2773.03
      29 2770.63    33.4 2767.16    38.7 2763.74      42 2762.87    44.9 2762.41
    55.2 2762.22    58.9 2761.83    61.8 2761.52    64.7  2761.5    69.92761.836
      76 2761.23    90.2 2761.37      92  2761.6    94.3 2762.45    95.9 2763.37
   102.5  2768.2   104.4 2769.04   107.7 2770.08   118.2 2771.43   127.1 2775.35
   132.8 2777.04   143.7 2780.93   162.2  2785.7   186.9 2791.43     200 2793.65
#Mann= 3, -1 ,  0
       0     0.1       0    58.9   0.045       0    69.9     0.1       0
Bank Sta=58.9,69.9
XS Rating Curve= 0 ,0
Exp/Cntr(USF)=0,0
Exp/Cntr=0.3,0.1

Type RM Length L Ch R = 1 ,1983    ,193.4,196.5,200.3
XS GIS Cut Line= 3
2202556.53872198576575.4705260072202571.89963846576627.313619119
2202641.54101472576732.150358142
#Sta/Elev= 30
       0 2779.82       6 2776.37    18.5  2768.3    26.9 2763.41      31 2761.37
    36.5 2759.09    39.7 2757.87    43.5 2756.77    47.7 2756.17    61.1 2755.31
    65.9 2754.29   70.382752.512    75.5 2751.69    85.1 2751.71    89.9  2751.9
   91.492752.502    97.9 2755.53   104.7 2757.93   109.1 2759.99   119.6 2765.54
   126.9 2768.94   133.5 2771.27   142.2 2773.35   147.9 2775.18   156.6  2776.4
   162.4 2776.63   165.3 2776.99   168.1 2777.56   176.8 2780.12   179.9 2780.74
#Mann= 3, -1 ,  0
       0     0.1       0   70.38   0.045       0   91.49     0.1       0
Bank Sta=70.38,91.49
XS Rating Curve= 0 ,0
Exp/Cntr(USF)=0,0
Exp/Cntr=0.3,0.1

Type RM Length L Ch R = 1 ,1787    ,278.9,280.6,278.8
XS GIS Cut Line= 3
2202382.49164931 576635.379547312202417.69374957576771.067642863
2202484.89775916576828.031041467
#Sta/Elev= 30
       0 2768.81     1.9 2768.58       6 2766.64    18.4 2755.91    22.5 2752.78
    26.7 2749.83    38.9 2742.06    51.4 2737.35   57.342736.915    63.8 2736.06
      68 2736.13   77.082736.916    84.9  2737.5    92.8 2738.53   102.3 2739.03
   113.4  2740.6   125.8 2740.57   138.2 2740.19   143.4 2740.44   148.7 2740.19
   154.8 2740.19   160.5 2740.92   164.4 2742.24   174.7 2747.71   180.6 2751.58
   190.6 2759.56   194.5 2761.96   201.1 2764.63   222.1 2771.77   228.3 2774.06
#Mann= 3, -1 ,  0
       0     0.1       0   57.34   0.045       0   77.08     0.1       0
Bank Sta=57.34,77.08
XS Rating Curve= 0 ,0
Exp/Cntr(USF)=0,0
Exp/Cntr=0.3,0.1

Type RM Length L Ch R = 1 ,1506    ,226.3,220.5,213.6
XS GIS Cut Line= 3
2202155.27809308576740.9858480942202189.20011696576896.515127431
2202260.24435567576988.680626297
#Sta/Elev= 30
       0 2734.58    16.6 2725.29    28.9 2721.29      37 2720.96    53.4 2721.76
    61.6 2723.17    73.9 2723.22   80.972719.564    82.1 2719.06    90.3  2718.8
    94.4  2718.9   97.712719.562   102.5 2720.63   106.6 2720.97   118.9 2721.13
     123 2721.56   127.1 2723.19   135.3 2729.07   139.4 2730.41   155.5 2730.46
   170.1 2731.74   187.4 2731.88   190.3  2732.1   193.2 2732.87   200.4  2735.7
   205.5 2738.73   212.6 2741.94   235.9 2755.86   249.2 2762.68   275.6 2770.27
#Mann= 3, -1 ,  0
       0     0.1       0   80.97   0.045       0   97.71     0.1       0
Bank Sta=80.97,97.71
XS Rating Curve= 0 ,0
Exp/Cntr(USF)=0,0
Exp/Cntr=0.3,0.1

Type RM Length L Ch R = 1 ,1286    ,130.6,137.7,137.6
XS GIS Cut Line= 3
2201928.70457503576888.1946310052202056.71221234576976.519900752
2202110.47542002577082.766239722
#Sta/Elev= 30
       0 2725.16     1.7 2724.49     8.8 2723.08    22.9 2721.68    26.2 2720.88
    29.9  2719.7    33.4    2717    36.9 2713.66    38.2 2712.95    43.1 2712.06
      48 2711.66   60.532708.168    63.6 2707.54    67.4  2707.3   77.452708.168
    86.8 2710.42   101.4 2709.33   112.5 2710.12   121.1 2711.45   135.5 2711.91
   142.6 2712.89   149.9 2715.51   169.7  2724.8   178.7 2727.53   187.6 2731.31
   206.2 2737.28     228 2743.43   241.4 2749.68   250.9 2753.23   274.6 2763.71
#Mann= 3, -1 ,  0
       0     0.1       0   60.53   0.045       0   77.45     0.1       0
Bank Sta=60.53,77.45
XS Rating Curve= 0 ,0
Exp/Cntr(USF)=0,0
Exp/Cntr=0.3,0.1

Type RM Length L Ch R = 1 ,1148    ,170.2,171.8,169.6
XS GIS Cut Line= 2
2201905.02162324576886.7348516692201945.87104209577136.567502876
#Sta/Elev= 30
       0  2727.1     6.5 2726.67    11.8 2724.87    22.3 2719.31    25.8 2717.95
    34.9 2712.66      39 2710.73    43.2 2709.54    57.3 2707.41    67.6 2704.98
    74.5 2704.56    95.4 2705.01    99.8 2704.52   103.8 2703.58   116.3 2703.53
   124.1 2702.73   140.3 2703.61   148.4 2702.49   156.5 2702.63   160.5 2701.97
   164.6 2701.87  167.42 2702.64   176.8 2704.88     193    2706     197 2706.86
   201.1 2708.94   209.2 2714.05   213.2 2717.19   237.6  2734.4   253.2  2743.9
#Mann= 4, -1 ,  0
       0    0.08       0      90     0.1       0   156.5   0.045       0
  167.42     0.1       0
Bank Sta=156.5,167.42
XS Rating Curve= 0 ,0
Exp/Cntr(USF)=0,0
Exp/Cntr=0.3,0.1

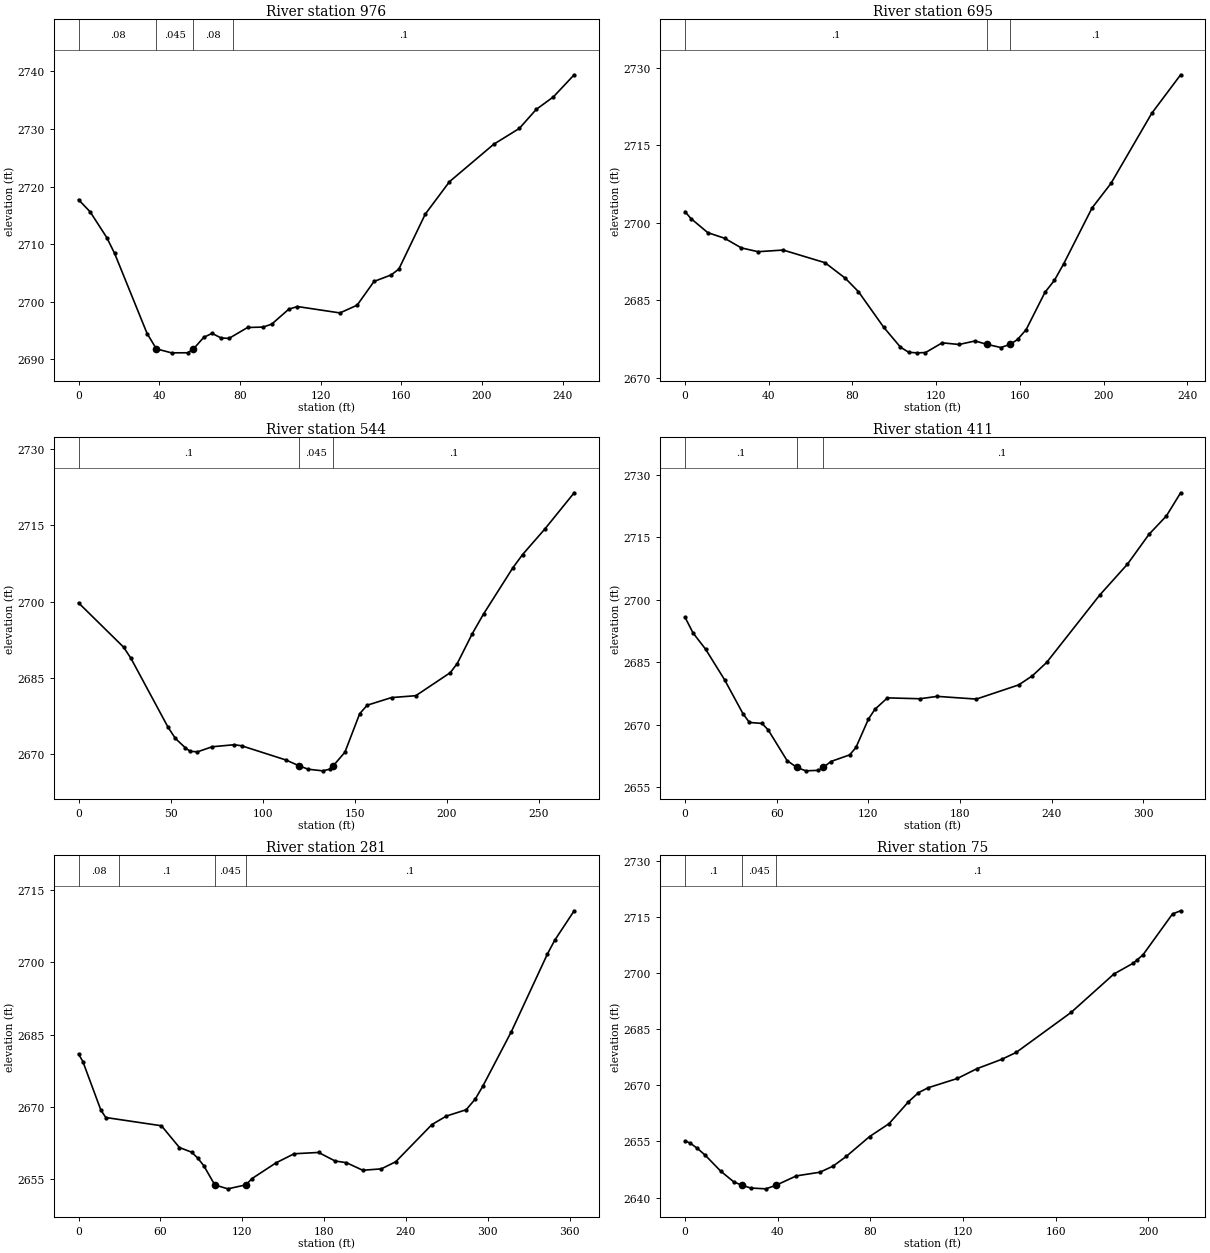
Type RM Length L Ch R = 1 ,976     ,287.4,280.8,280
XS GIS Cut Line= 3
2201805.81724321576907.3957766022201798.59608571576973.658131018
2201856.94731131577142.949011745
#Sta/Elev= 30
       0 2717.72     5.8 2715.59      14 2711.14    17.9 2708.38      34 2694.47
    38.62691.809    46.1 2691.12    54.1 2691.13      572691.804    62.1 2693.82
    66.2  2694.5    70.7  2693.7    74.6 2693.63    83.8 2695.52    91.5 2695.59
    95.8 2696.11   104.2 2698.69   108.5 2699.16   129.6 2698.05   138.1 2699.39
   146.5 2703.52     155 2704.65   158.8 2705.67   171.9 2715.21   183.9 2720.84
   205.8 2727.33   218.5 2730.08   226.9 2733.39   235.4 2735.56   245.7  2739.4
#Mann= 4, -1 ,  0
       0    0.08       0    38.6   0.045       0      57    0.08       0
   76.65     0.1       0
Bank Sta=38.6,57
XS Rating Curve= 0 ,0
Exp/Cntr(USF)=0,0
Exp/Cntr=0.3,0.1

Type RM Length L Ch R = 1 ,695     ,150.2,151.4,151.1
XS GIS Cut Line= 3
2201596.27914398576982.3182900672201591.12576671577145.044349009
2201625.25639041577210.721009882
#Sta/Elev= 30
       0 2702.15     2.9 2700.78    10.9 2698.07    18.9 2696.99    26.9 2695.12
    34.9 2694.38    46.9  2694.7    66.9 2692.25    76.6 2689.24    82.9 2686.63
    94.9 2679.77   102.9 2675.91   106.9 2674.89   110.9 2674.79   114.9 2674.84
   122.9 2676.73   130.9 2676.41   138.6 2677.09  144.422676.421   150.9 2675.82
  155.382676.438   158.9 2677.38     163 2679.29     172 2686.52   176.5 2688.83
     181 2692.09   194.5 2702.87   203.5  2707.6     223 2721.19   236.8 2728.65
#Mann= 3, -1 ,  0
       0     0.1       0  144.42   0.045       0  155.38     0.1       0
Bank Sta=144.42,155.38
XS Rating Curve= 0 ,0
Exp/Cntr(USF)=0,0
Exp/Cntr=0.3,0.1

Type RM Length L Ch R = 1 ,544     ,134.3,133.3,129.9
XS GIS Cut Line= 3
2201448.91792659577000.677736886 2201440.1850719577156.504266143
2201486.90785952577259.550414181
#Sta/Elev= 30
       0 2699.74    24.5 2691.01    28.5  2688.8    48.6 2675.27    52.6 2673.05
    58.1 2671.18    60.6 2670.52    64.6 2670.41    72.6 2671.41    84.6 2671.81
    88.6  2671.6   112.7  2668.8  119.832667.656   124.7 2666.99   132.7 2666.67
   136.7 2667.02  138.222667.602   144.7 2670.35   152.7 2677.91   156.8 2679.59
     170 2681.09   183.2 2681.46   201.9 2685.99   205.7 2687.79   213.9 2693.69
     220 2697.55   235.9 2706.63   241.2 2709.25   253.3 2714.28   269.2  2721.4
#Mann= 3, -1 ,  0
       0     0.1       0  119.83   0.045       0  138.22     0.1       0
Bank Sta=119.83,138.22
XS Rating Curve= 0 ,0
Exp/Cntr(USF)=0,0
Exp/Cntr=0.3,0.1

Type RM Length L Ch R = 1 ,411     ,131.6,130,127.8
XS GIS Cut Line= 3
2201294.34700032577024.0177902642201325.45285618577160.883556081
2201452.98686524577293.601874448
#Sta/Elev= 30
       0 2695.86     5.3 2692.06    13.5 2688.17    25.9 2680.85    38.1  2672.6
    42.2 2670.59    50.4 2670.36    54.5 2668.78    66.8 2661.45   73.272659.783
    79.1 2658.98    87.3  2659.1   90.542659.784    95.5 2661.22   107.8 2662.81
   111.9 2664.59   120.1 2671.42   124.3 2673.74   132.5 2676.49   153.8 2676.28
   165.1 2676.85   190.7  2676.2   218.4  2679.6   227.4 2681.79   236.7 2684.99
   271.3  2701.1   289.6 2708.58   303.7 2715.74   315.1 2720.16   324.4 2725.71
#Mann= 3, -1 ,  0
       0     0.1       0   73.27   0.045       0   90.54     0.1       0
Bank Sta=73.27,90.54
XS Rating Curve= 0 ,0
Exp/Cntr(USF)=0,0
Exp/Cntr=0.3,0.1

Type RM Length L Ch R = 1 ,281     ,203.4,205.5,190.5
XS GIS Cut Line= 3
2201148.34129792577058.3293244652201232.82886511577235.624955273
2201358.91638787577345.071485176
#Sta/Elev= 30
       0 2680.99     3.2 2679.41    16.4 2669.35      20 2667.82    60.8 2666.11
      74  2661.6    82.9 2660.64    87.3 2659.45    91.8 2657.85   99.942653.846
   109.5 2653.04   122.8 2653.87   127.2 2655.17   144.9 2658.44   158.1 2660.31
     176 2660.58   188.1 2658.81   196.4 2658.46   208.4 2656.89     222 2657.18
   232.6 2658.66   259.1 2666.36   269.7 2668.12   284.2 2669.43   290.9 2671.65
   296.3 2674.25   317.4 2685.64   343.8 2701.71   349.1 2704.53   363.4 2710.66
#Mann= 4, -1 ,  0
       0    0.08       0      30     0.1       0   99.94   0.045       0
   122.8     0.1       0
Bank Sta=99.94,122.8
XS Rating Curve= 0 ,0
Exp/Cntr(USF)=0,0
Exp/Cntr=0.3,0.1

Type RM Length L Ch R = 1 ,75      ,14.2,11.6,15.4
XS GIS Cut Line= 3
2201142.84000139 577320.87197797 2201190.2028272577382.315643881
2201319.49054089577425.838240568
#Sta/Elev= 30
       0 2655.13     2.2 2654.59     5.4 2653.12     8.7 2651.35    15.4 2647.07
    21.1 2644.17    24.72643.257    28.4 2642.54    34.9 2642.32    39.22643.246
    48.1 2645.79    58.2 2646.76    63.9 2648.38    69.6 2650.98    79.7 2656.31
    88.1 2659.76    96.5 2665.62   100.8 2668.05     105 2669.38   117.6 2671.86
   126.1 2674.49   136.7 2676.97     143 2678.83   166.7 2689.53   185.2 2699.82
   193.6 2702.74   195.1 2703.53   197.8 2704.99   210.5  2715.9     214 2716.74
#Mann= 3, -1 ,  0
       0     0.1       0    24.7   0.045       0    39.2     0.1       0
Bank Sta=24.7,39.2
XS Rating Curve= 0 ,0
Exp/Cntr(USF)=0,0
Exp/Cntr=0.3,0.1

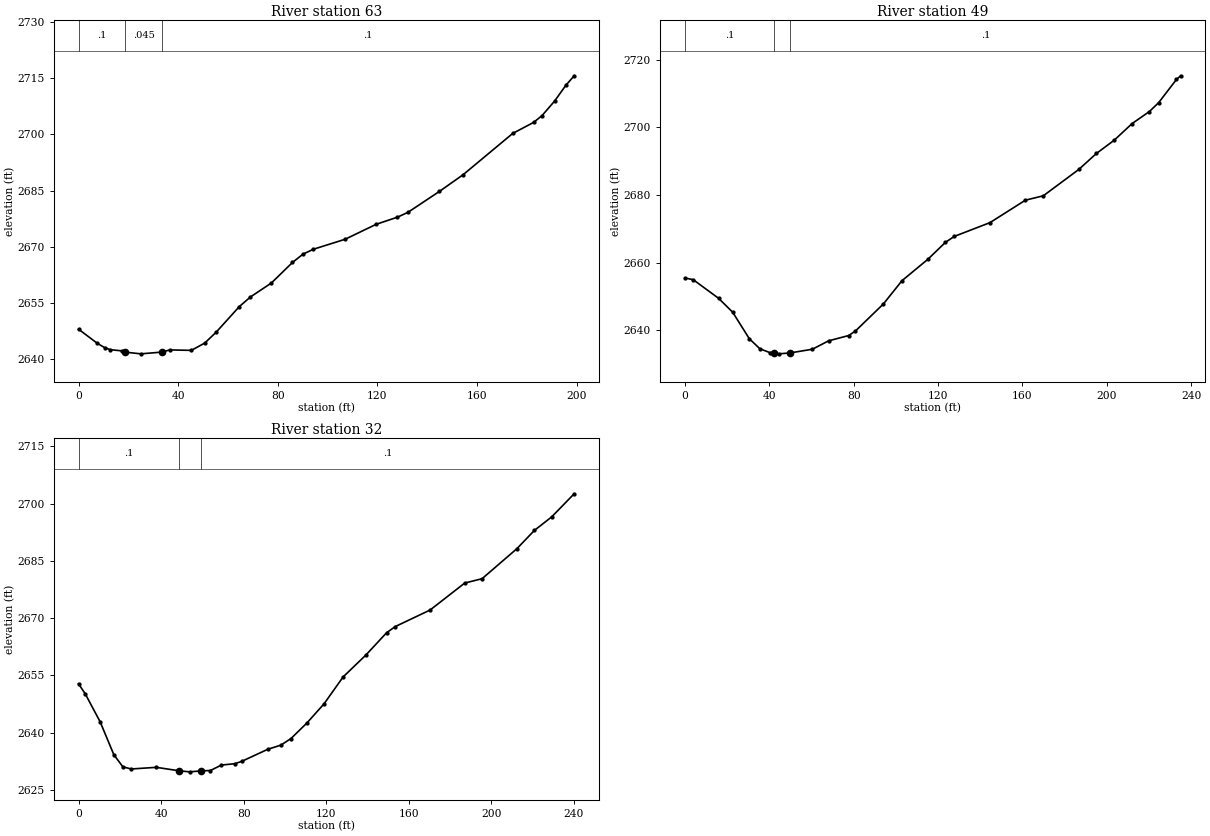
Type RM Length L Ch R = 1 ,63      ,13.6,14.5,18.9
XS GIS Cut Line= 4
2201144.24049676577338.531287703 2201164.9953667577370.224535042
2201191.35966094577385.0895094582201315.60840936577426.038306904
#Sta/Elev= 30
       0 2647.91     7.6  2644.1    10.5 2642.97    12.7 2642.43    17.5  2642.1
   18.66 2641.77      25 2641.31    33.6 2641.78    36.6 2642.36    45.3 2642.24
    50.7 2644.21    55.3 2647.13    64.5 2653.92      69 2656.52    77.4 2660.25
    85.9 2665.76    90.1 2667.98    94.3  2669.3     107 2671.96   119.5 2675.97
     128 2677.87   132.2 2679.15   144.9 2684.78   154.4 2689.24   174.3 2700.28
   182.7 2703.24   186.1 2705.07   191.1 2708.93   195.6 2713.13198.9732 2715.71
#Mann= 3, -1 ,  0
       0     0.1       0   18.66   0.045       0    33.6     0.1       0
Bank Sta=18.66,33.6
XS Rating Curve= 0 ,0
Exp/Cntr(USF)=0,0
Exp/Cntr=0.3,0.1

Type RM Length L Ch R = 1 ,49      ,17.3,17.1,17.7
XS GIS Cut Line= 4
2201139.80776414577317.3321323832201138.56237438577347.073774696
2201146.69036922577374.9529159872201314.09234654577430.059246385
#Sta/Elev= 30
       0 2655.48     3.9 2654.98    15.9 2649.49    22.6 2645.37    30.5 2637.53
    35.5 2634.55    40.3  2633.4    42.4 2633.32    44.5 2633.05    49.8 2633.32
    60.4 2634.41    68.1  2636.9    77.6 2638.46    80.8 2639.79    94.1 2647.82
   102.9 2654.69   115.1 2660.98   123.5 2666.03   127.7 2667.78   144.6 2671.85
   161.4 2678.49   169.9 2679.79   186.7 2687.57   195.1 2692.32   203.5 2696.22
     212 2701.15   220.2 2704.71   224.6 2707.34     233 2714.18     235 2715.28
#Mann= 3, -1 ,  0
       0     0.1       0    42.4   0.045       0    49.8     0.1       0
Bank Sta=42.4,49.8
XS Rating Curve= 0 ,0
Exp/Cntr(USF)=0,0
Exp/Cntr=0.3,0.1

Type RM Length L Ch R = 1 ,32      ,,,
XS GIS Cut Line= 4
2201135.39068361577315.452131616 2201121.0662002577324.790387834
2201127.10154005577371.1546481522201294.50351737 577426.26097855
#Sta/Elev= 30
       0 2652.82     3.2 2650.25    10.5 2642.84    17.1 2634.26    21.5 2631.06
    25.6 2630.51    37.7 2630.94    48.8 2630.03    53.8 2629.76    59.5 2630.01
    63.9 2630.11    69.2 2631.53    75.8  2631.9      79 2632.49    91.7 2635.67
      98 2636.75   102.9 2638.47   110.7 2642.59   118.9 2647.55   128.2 2654.63
   139.2 2660.35   149.2 2666.17   153.4  2667.8   170.3 2672.14   187.1 2679.21
   195.5 2680.35   212.4 2688.23   220.8 2692.98   229.2 2696.53   240.1 2702.59
#Mann= 3, -1 ,  0
       0     0.1       0    48.8   0.045       0    59.5     0.1       0
Bank Sta=48.8,59.5
XS Rating Curve= 0 ,0
Exp/Cntr(USF)=0,0
Exp/Cntr=0.3,0.1
LCMann Table=0

Chan Stop Cuts=-1
Use User Specified Reach Order=0
Composite Channel Slope=5